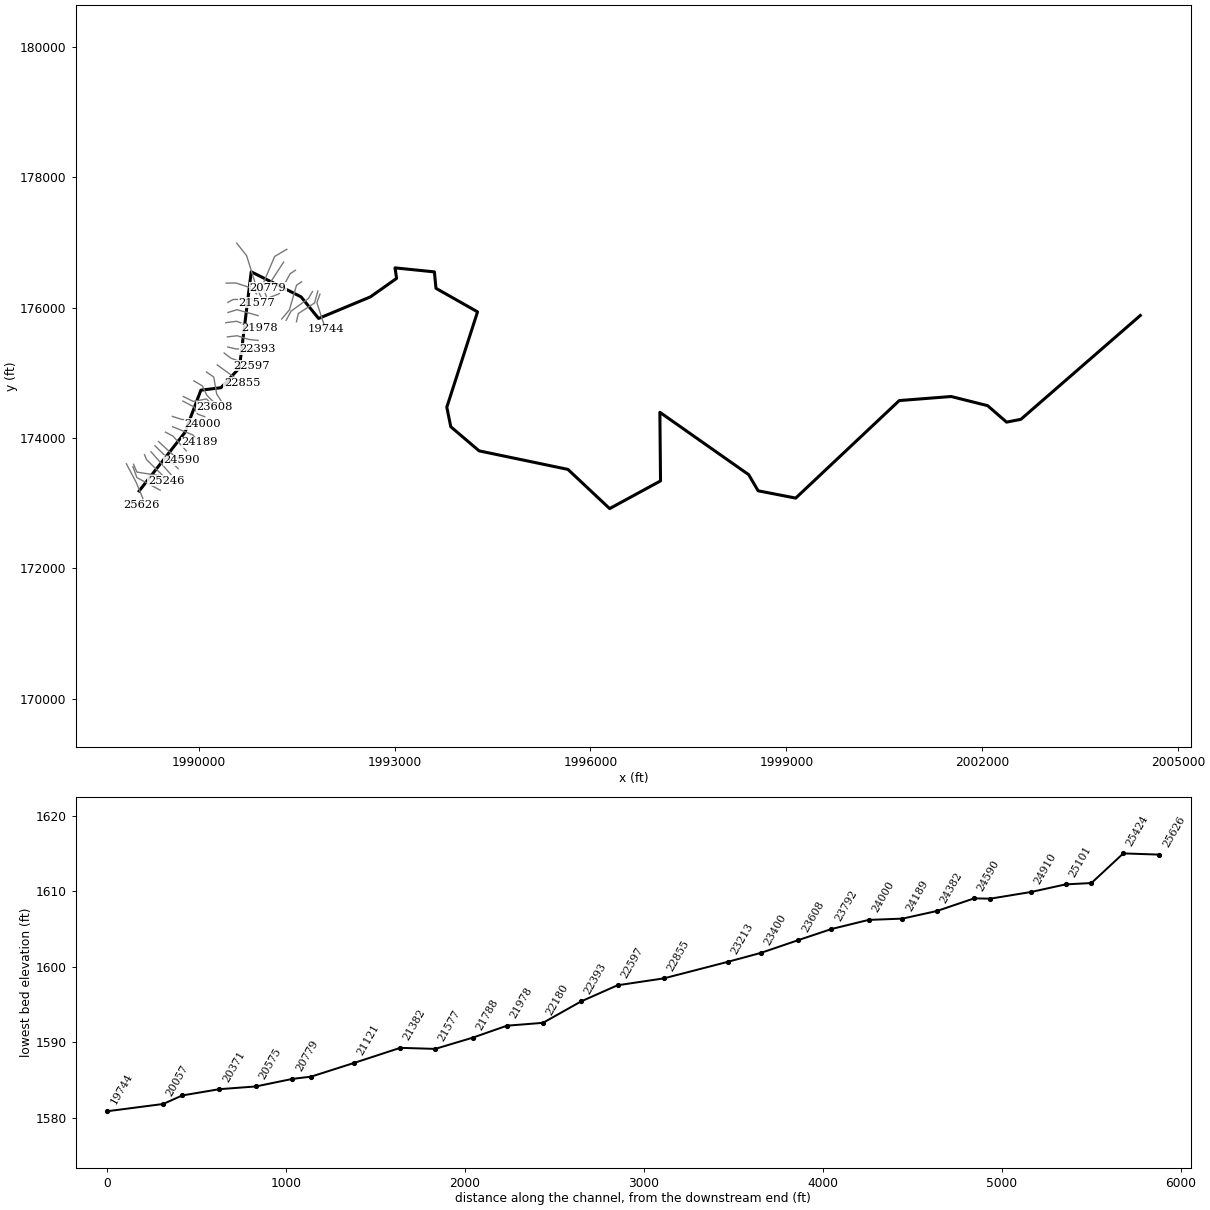
--- LICKCK.prj (project) ---

Proj Title=LICKCK
Current Plan=p01
Default Exp/Contr=0,0
English Units
Geom File=g01
Flow File=f01
Plan File=p01
BEGIN DESCRIPTION:
Stream Name: Lick Creek
Flood Zone: Approximate
Summers County, West Virginia
HEC-RAS Version: 5.0.7
Hydrology Method:
regression
Model Notes:
END DESCRIPTION:
DSS Export Rating Curves= 0
DSS Export Rating Curve Sorted= 0
DSS Export Volume Flow Curves= 0
DXF OffsetX= 0
DXF OffsetY= 0
DXF ScaleX= 0
DXF ScaleY= 0

--- LICKCK.p01 (plan) ---

Plan Title=Floodplain
Program Version=5.07
Short Identifier=Floodplain
Geom File=g01
Flow File=f01
Subcritical Flow
K Sum by GR= 0
Std Step Tol= 0.01
Critical Tol= 0.01
Num of Std Step Trials= 20
Max Error Tol= 0.3
Flow Tol Ratio= 0.001
Split Flow NTrial= 30
Split Flow Tol= 0.02
Split Flow Ratio= 0.02
Log Output Level= 0
Friction Slope Method= 1
Unsteady Friction Slope Method= 2
Unsteady Bridges Friction Slope Method= 1
Parabolic Critical Depth
Global Vel Dist= 0 , 0 , 0
Global Log Level= 0
CheckData=True
Encroach Param=-1 ,0,0, 0
Mapping Interval=1HOUR
Computation Time Step Use Courant=        0
Computation Time Step Use Time Series=    0
Computation Time Step Count To Double=0
Computation Time Step Max Doubling=0
Computation Time Step Max Halving=0
Computation Time Step Residence Courant=0
Run HTab= 0
Run UNet= 0
Run Sediment= 0
Run PostProcess= 0
Run WQNet= 0
Run RASMapper= 0
UNET Theta= 0
UNET Theta Warmup= 0
UNET ZTol= 0
UNET ZSATol= 0
UNET MxIter= 0
UNET Max Iter WO Improvement= 0
UNET MaxInSteps= 0
UNET DtIC= 0
UNET DtMin= 0
UNET MaxCRTS= 0
UNET WFStab= 0
UNET SFStab= 0
UNET WFX= 1
UNET SFX= 1
UNET 1D Methodology=Finite Difference
UNET DSS MLevel= 1
UNET Pardiso=0
UNET DZMax Abort= 0
UNET Use Existing IB Tables= 0
UNET Froude Reduction=False
UNET Froude Limit= 0
UNET Froude Power= 0
UNET D1 Cores= 0
UNET D2 Coriolis=0
UNET D2 Cores= 0
UNET D2 Theta= 1
UNET D2 Theta Warmup= 1
UNET D2 Z Tol= 0.01
UNET D2 Volume Tol= 0.01
UNET D2 Max Iterations= 20
UNET D2 Equation= 0
UNET D2 RampUpFraction=0.1
UNET D2 TimeSlices= 1
UNET D2 BCVolumeCheck=0
UNET D1D2 MaxIter= 0
UNET D1D2 ZTol=0.01
UNET D1D2 QTol=0.1
UNET D1D2 MinQTol=1
Write IC File= 0
Write IC File at Fixed DateTime=0
Write IC File at Sim End=0
Echo Input=False
Echo Parameters=False
Echo Output=False
Write Detailed= 0
HDF Write Warmup=0
HDF Write Time Slices=0
HDF Flush=0
HDF Face Node Velocities=0
HDF Compression= 1
HDF Chunk Size= 1
HDF Spatial Parts= 1
HDF Use Max Rows=0
HDF Fixed Rows= 1
Calibration Method= 0
Calibration Iterations= 20
Calibration Max Change=0.05
Calibration Tolerance=0.2
Calibration Maximum=1.5
Calibration Minimum=0.5
Calibration Optimization Method= 1
WQ AD Non Conservative
WQ ULTIMATE=-1
WQ Max Comp Step=1HOUR
WQ Output Interval=15MIN
WQ Output Selected Increments= 0
WQ Output face flow=0
WQ Output face velocity=0
WQ Output face area=0
WQ Output face dispersion=0
WQ Output cell volume=0
WQ Output cell surface area=0
WQ Output cell continuity=0
WQ Output cumulative cell continuity=0
WQ Output face conc=0
WQ Output face dconc_dx=0
WQ Output face courant=0
WQ Output face peclet=0
WQ Output face adv mass=0
WQ Output face disp mass=0
WQ Output cell mass=0
WQ Output cell source sink temp=0
WQ Output nsm pathways=0
WQ Output nsm derived pathways=0
WQ Output MaxMinRange=-1
WQ Daily Max Min Mean=-1
WQ Daily Range=0
WQ Daily Time=0
WQ Create Restart=0
WQ Fixed Restart=0
WQ System Summary=0
WQ Write To DSS=0
WQ Use Fixed Temperature=0
Sorting and Armoring Iterations= 10
XS Update Threshold= 0.02
Bed Roughness Predictor= 0
Hydraulics Update Threshold= 0.02
Energy Slope Method= 1
Volume Change Method= 1
Sediment Retention Method= 0
XS Weighting Method= 0
Number of US Weighted Cross Sections= 1
Number of DS Weighted Cross Sections= 1
Upstream XS Weight=0
Main XS Weight=1
Downstream XS Weight=0
Number of DS XS's Weighted with US Boundary= 1
Upstream Boundary Weight= 1
Weight of XSs Associated with US Boundary= 0
Number of US XS's Weighted with DS Boundary= 1
Downstream Boundary Weight= 0.5
Weight of XSs Associated with DS Boundary= 0.5
Percentile Method= 0
Sediment Output Level= 3
Mass or Volume Output= 0
Output Increment Type= 1
Profile and TS Output Increment= 1
XS Output Flag= 0
XS Output Increment= 10
Write Gradation File= 0
Read Gradation Hotstart= 0
Write HDF5 File= 1
Write Binary Output= 1
Write DSS Sediment File= 0
SV Curve= 0
Specific Gage Flag= 0

--- LICKCK.f01 (steady flow) ---

Flow Title=Flows
Program Version=5.07
Number of Profiles= 6
Profile Names=01pct,10pct,04pct,02pct,0_2pct,01plus
River Rch & RM=LICKCK,Main            ,25626
    1641     903    1178    1402    2247    2427
River Rch & RM=LICKCK,Main            ,25246
    1902    1053    1369    1627    2597    2812
River Rch & RM=LICKCK,Main            ,20884
    2546    1426    1844    2184    3459    3766
River Rch & RM=LICKCK,Main            ,16595
    2981    1679    2165    2560    4037    4408
River Rch & RM=LICKCK,Main            ,14773
    3313    1874    2412    2849    4478    4901
Boundary for River Rch & Prof#=LICKCK,Main            , 1
Up Type= 0
Dn Type= 3
Dn Slope=0.022312
Boundary for River Rch & Prof#=LICKCK,Main            , 2
Up Type= 0
Dn Type= 3
Dn Slope=0.022312
Boundary for River Rch & Prof#=LICKCK,Main            , 3
Up Type= 0
Dn Type= 3
Dn Slope=0.022312
Boundary for River Rch & Prof#=LICKCK,Main            , 4
Up Type= 0
Dn Type= 3
Dn Slope=0.022312
Boundary for River Rch & Prof#=LICKCK,Main            , 5
Up Type= 0
Dn Type= 3
Dn Slope=0.022312
Boundary for River Rch & Prof#=LICKCK,Main            , 6
Up Type= 0
Dn Type= 3
Dn Slope=0.022312
DSS Import GetInterval= 0
DSS Import GetPeak= 0
DSS Import FillOption= 0

--- LICKCK.g01 (geometry) ---

Geom Title=Geometry
Program Version=5.07

River Reach=LICKCK          ,Main
Reach XY= 30
     1989089.446      173186.0051989789.32585636174082.637071822
     1990034.194      174731.884     1990342.321      174769.989
     1990624.149       175073.07     1990805.141      176548.261
1991568.26662763176164.301228729     1991836.979      175832.363
1992631.12014345 176164.06576646     1993031.336      176447.163
     1993007.031      176608.622     1993610.329      176546.881
     1993634.201      176295.145     1994270.667      175933.781
     1993800.267      174471.194     1993860.684      174171.194
     1994295.059      173800.8811995654.68117373173516.665748587
      1996293.67      172915.465     1997072.836      173340.118
     1997062.698      174392.733     1998422.707      173435.838
     1998567.239      173188.442      1999142.76      173076.463
     2000728.697      174572.557     2001522.968      174635.057
     2002081.562      174494.432     2002371.926      174241.828
     2002590.676      174284.797      2004419.95      175878.401

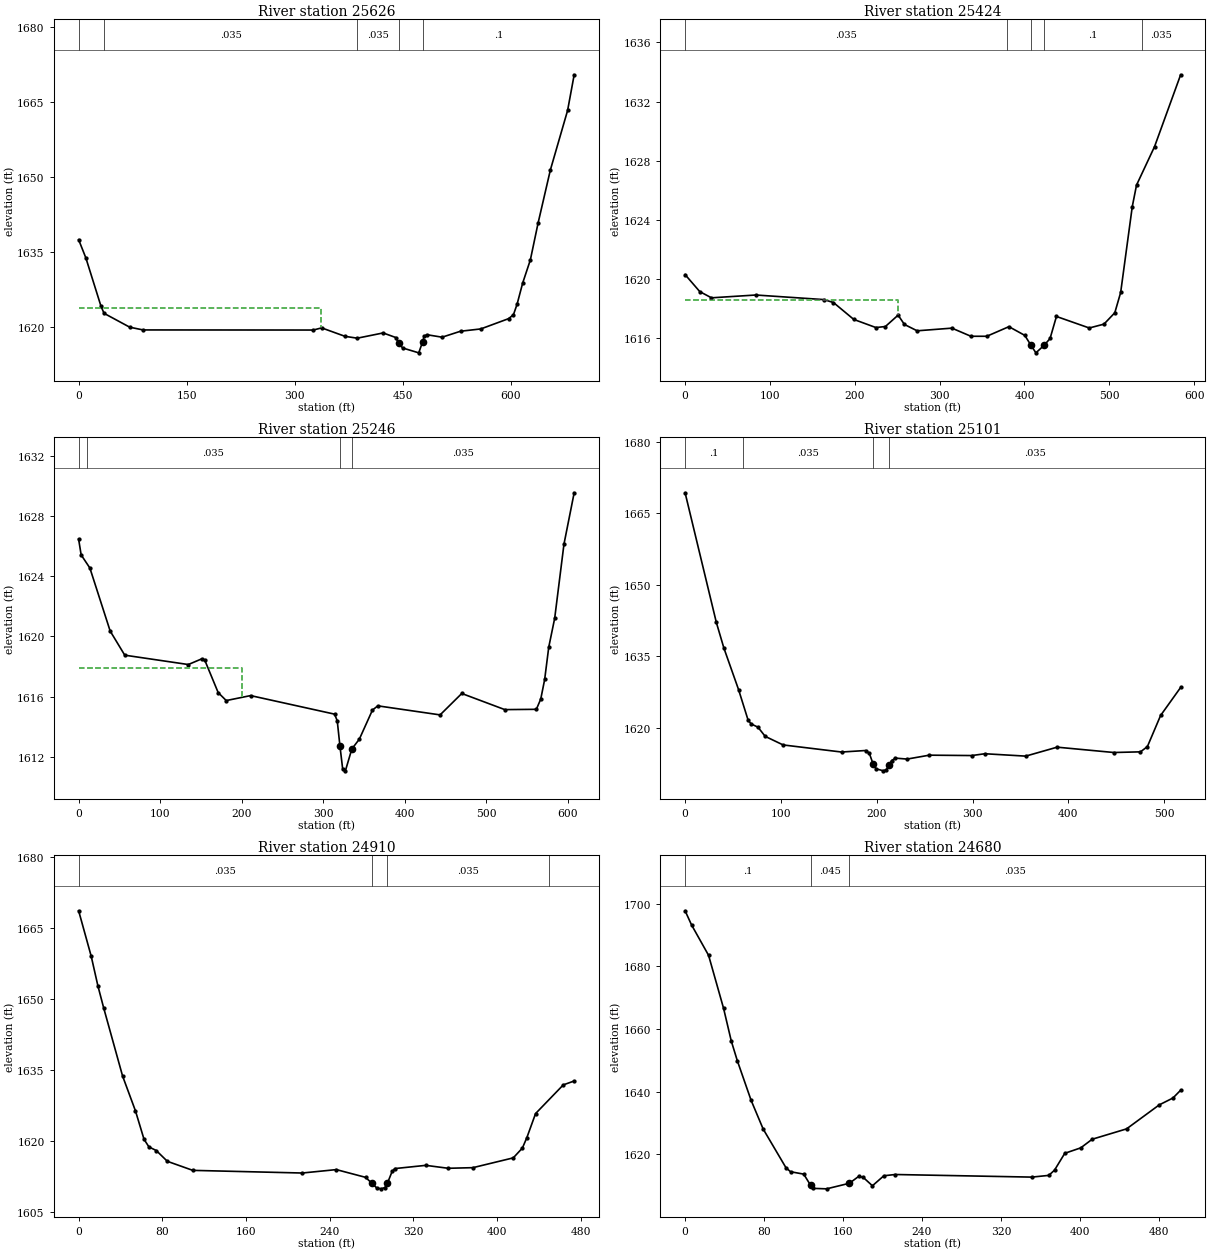
Type RM Length L Ch R = 1 ,25626   ,201.2,202.1,201.2
XS GIS Cut Line= 4
1988893.22018751173602.6208601461989044.95671452173314.502097546
1989147.01759281173069.7366283791989119.92178441172976.707686223
#Sta/Elev= 30
       0 1637.48      10 1633.85    31.1 1624.14    35.3 1622.75    70.9 1619.98
    89.4 1619.43   325.6 1619.41   337.3 1619.84   369.7 1618.15   386.7 1617.78
   422.6 1618.83   440.4  1617.9     444 1616.79   449.7 1615.82     472 1614.85
   477.3 1617.01   479.5 1618.14   483.1 1618.48   504.4 1617.98     530 1619.17
   558.1 1619.63   596.6 1621.68   603.4 1622.46   608.4 1624.53   616.3 1628.83
   626.9 1633.43   637.6 1640.78   654.7 1651.43   678.6 1663.33687.7184 1670.46
#Mann= 5 ,-1 , 0
       0      .1       0    35.3    .035       0   386.7    .035       0
     444    .045       0   477.3      .1       0
#XS Ineff= 2 , 0
          335.97 1623.77
Permanent Ineff=
       F       F
Bank Sta=444,477.3
XS Rating Curve= 0 ,0
Exp/Cntr(USF)=0,0
Exp/Cntr=0.3,0.1

Type RM Length L Ch R = 1 ,25424   ,167.5,178.2,180.8
XS GIS Cut Line= 3
1988993.54332059 173559.296692451989054.24498488173391.027958418
1989410.44927188 173197.80458902
#Sta/Elev= 30
       0  1620.3    17.3 1619.15    31.1 1618.73    83.4 1618.92   163.6 1618.61
   174.9 1618.41   198.8 1617.27   224.9 1616.72   236.1 1616.79   251.1 1617.56
   258.5 1616.93   273.5  1616.5   314.5 1616.68   336.9 1616.13   355.6 1616.13
   381.7 1616.78   400.4 1616.19   407.8 1615.51   413.5 1615.01   423.2 1615.52
   430.2 1615.98   437.7 1617.47   476.4 1616.69   493.7 1616.95   506.5 1617.72
   513.4 1619.09   527.1  1624.9   532.1 1626.35   553.4 1628.96   584.1 1633.81
#Mann= 5 ,-1 , 0
       0    .035       0  378.88      .1       0   407.8    .045       0
   423.2      .1       0  538.88    .035       0
#XS Ineff= 2 , 0
          251.15 1618.59
Permanent Ineff=
       F       F
Bank Sta=407.8,423.2
XS Rating Curve= 0 ,0
Exp/Cntr=0.3,0.1

Type RM Length L Ch R = 1 ,25246   ,156.9,144.7,134.6
XS GIS Cut Line= 4
1989003.48409559173595.2880547181989054.24498488 173475.38961376
1989394.31591509173421.8175597511989500.86551316173341.403455275
#Sta/Elev= 30
       0 1626.45     3.1 1625.41    13.8 1624.54    38.7 1620.36    56.6 1618.76
   134.6 1618.14   151.2 1618.52   154.6 1618.45   171.2 1616.28   181.1 1615.75
     211 1616.08     314 1614.85   317.3 1614.41   320.6 1612.74     324  1611.2
   327.3 1611.09   335.2 1612.54   344.4 1613.19   360.5 1615.12   367.1  1615.4
   443.5  1614.8   470.1 1616.22   522.9 1615.15   561.6 1615.17     567 1615.85
   571.8 1617.15   576.8 1619.29   584.1 1621.21   595.5 1626.13     608 1629.53
#Mann= 4 ,-1 , 0
       0      .1       0      10    .035       0   320.6    .045       0
   335.2    .035       0
#XS Ineff= 2 , 0
             200  1617.9
Permanent Ineff=
       F       F
Bank Sta=320.6,335.2
XS Rating Curve= 0 ,0
Exp/Cntr=0.3,0.1

Type RM Length L Ch R = 1 ,25101   ,192.9,191.5,187
XS GIS Cut Line= 3
1989170.75325462173741.3756139181989202.26807905173665.740035283
1989513.21434677173361.096732446
#Sta/Elev= 30
       0  1669.3    32.6 1642.08    40.5 1636.68    55.8 1627.97    65.8 1621.53
      69 1620.76    76.1 1620.07    83.6 1618.15   102.3 1616.35   163.3 1614.86
   188.6 1615.18   192.3 1614.57   196.41612.264   199.3 1611.34     207 1610.91
   210.1 1611.16   213.2 1612.17   215.5 1613.05   219.5 1613.58   231.7 1613.38
   254.9  1614.2   299.2 1614.12   312.9  1614.5   355.5    1614   388.3 1615.88
   447.5 1614.76   475.3  1614.9   482.5    1616   496.3 1622.54   517.2 1628.42
#Mann= 4 ,-1 , 0
       0      .1       0      60    .035       0   196.4    .045       0
   213.2    .035       0
Bank Sta=196.4,213.2
XS Rating Curve= 0 ,0
Exp/Cntr(USF)=0,0
Exp/Cntr=0.3,0.1

Type RM Length L Ch R = 1 ,24910   ,231.7,229.3,208.3
XS GIS Cut Line= 2
1989270.55019865173787.5973564171989581.49646637173430.429346195
#Sta/Elev= 30
       0 1668.62      12 1659.04    18.4 1652.78    23.9 1648.14      42 1633.73
    54.3 1626.38    62.5 1620.37    67.2 1618.76    74.2    1618    84.8 1615.72
   109.1 1613.81   213.7 1613.25   246.3 1613.97   274.2 1612.34   280.5 1611.04
   284.9  1610.1   289.2 1609.91   292.8 1610.19   295.1 1611.09   299.7 1613.63
   302.3 1614.19   331.8 1614.87   353.2 1614.25   376.8 1614.38   415.4 1616.45
   424.1 1618.52   428.4 1620.73   436.7  1625.8   463.2 1631.86   473.6 1632.68
#Mann= 4 ,-1 , 0
       0    .035       0   280.5    .045       0   295.1    .035       0
     450      .1       0
Bank Sta=280.5,295.1
XS Rating Curve= 0 ,0
Exp/Cntr(USF)=0,0
Exp/Cntr=0.3,0.1

Type RM Length L Ch R = 1 ,24680   ,88.8,90.2,99.2
XS GIS Cut Line= 2
1989330.42836507173880.0408414161989687.59637529173527.074807785
#Sta/Elev= 30
       0 1697.69     6.5  1693.2    23.8 1683.48      39 1666.56    46.8 1656.15
    52.9 1649.89    66.9 1637.23    79.1 1628.09   102.2 1615.76   106.8 1614.48
   120.2 1613.71   127.2 1610.13   129.9 1609.17   143.4 1609.02   166.5  1610.8
     176 1613.02   180.6 1612.64   189.8    1610   201.4 1613.19   212.9 1613.59
   351.3 1612.76   368.5 1613.31   374.3 1614.97   384.7 1620.35   400.9 1622.09
   412.5 1624.84   447.3 1628.14   480.4 1635.79   494.3 1637.98   502.1 1640.47
#Mann= 3 ,-1 , 0
       0      .1       0   127.2    .045       0   166.5    .035       0
Bank Sta=127.2,166.5
XS Rating Curve= 0 ,0
Exp/Cntr(USF)=0,0
Exp/Cntr=0.3,0.1

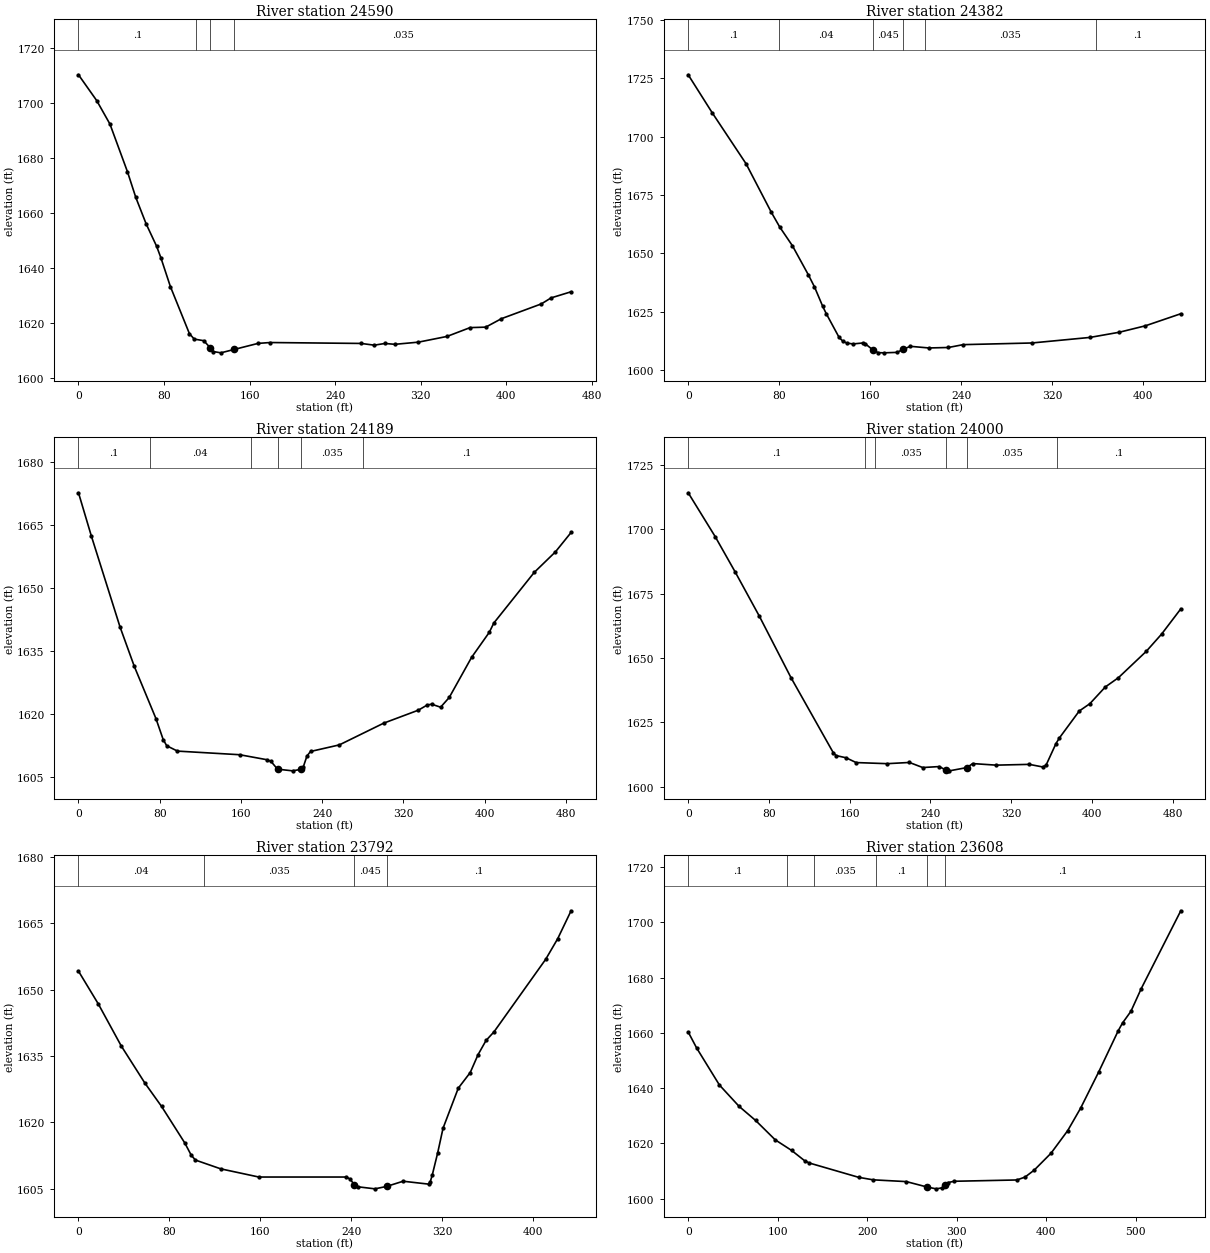
Type RM Length L Ch R = 1 ,24590   ,209.6,207.7,205.6
XS GIS Cut Line= 3
1989385.84328368173943.6757644511989637.99274751173711.620357419
1989743.71235482173659.665409347
#Sta/Elev= 30
       0 1710.24      17 1700.87    29.4 1692.31    45.8 1674.94    53.6 1665.59
    63.3 1655.94      73 1647.88      77 1643.69    85.9 1633.19   103.7 1616.05
   108.2 1614.06   117.1 1613.48   123.3 1610.86   126.1 1609.53   133.1 1609.06
   145.6  1610.3   167.9  1612.5   179.2 1612.81   264.3 1612.48   276.5 1611.85
   286.5 1612.47   295.8 1612.16   317.8 1612.95   344.5 1615.03   366.1 1618.24
   380.7 1618.41   395.4 1621.49   432.7 1626.87   441.8 1629.05   460.5 1631.28
#Mann= 4 ,-1 , 0
       0      .1       0     110    .035       0   123.3    .045       0
   145.6    .035       0
Bank Sta=123.3,145.6
XS Rating Curve= 0 ,0
Exp/Cntr=0.3,0.1

Type RM Length L Ch R = 1 ,24382   ,182.8,193.2,201.3
XS GIS Cut Line= 3
1989492.68093921174087.9888379461989606.22645092174027.914890156
1989810.44251324173801.575421091
#Sta/Elev= 30
       0 1726.45    21.2 1710.13    50.9 1688.36    73.1 1667.59    80.5 1661.28
    91.7 1653.23   105.6 1640.89   111.1 1635.62   118.3 1627.34   121.4 1624.21
   132.7 1614.04   136.1 1612.32   139.7 1611.54     145 1611.21   153.4  1611.6
   155.9 1611.22   162.7 1608.54   167.1 1607.47   172.2 1607.39   183.8 1607.59
   189.2 1608.94   195.4 1610.18   211.7 1609.48   228.9 1609.68   241.9  1610.9
   302.3 1611.61   353.4 1613.99   379.2 1616.21   402.2 1618.97   433.3 1624.13
#Mann= 6 ,-1 , 0
       0      .1       0      80     .04       0   162.7    .045       0
   189.2     .04       0  208.46    .035       0  358.46      .1       0
Bank Sta=162.7,189.2
XS Rating Curve= 0 ,0
Exp/Cntr=0.3,0.1

Type RM Length L Ch R = 1 ,24189   ,184.6,189,195.8
XS GIS Cut Line= 3
1989601.47645608174171.4160478121989910.84874388174045.783795608
1990010.64375638173932.254703375
#Sta/Elev= 30
       0 1672.61    12.6 1662.37    40.9 1640.66      55 1631.24    76.3 1618.82
    83.4 1613.84    86.9 1612.35    97.5 1611.08   158.7 1610.22     186 1609.01
   189.6 1608.62     196 1606.78   210.8 1606.38   219.1 1606.73   221.5  1607.4
     225 1609.92   228.5 1610.99   256.9 1612.56   300.6 1617.74   334.7 1620.83
   343.5 1622.07   347.8 1622.25   356.6 1621.54   365.1 1623.85   387.1  1633.4
   404.6 1639.39     409 1641.58   448.8 1653.64   469.7 1658.54   485.1 1663.15
#Mann= 6 ,-1 , 0
       0      .1       0      70     .04       0     170    .035       0
     196    .045       0   219.1    .035       0     280      .1       0
Bank Sta=196,219.1
XS Rating Curve= 0 ,0
Exp/Cntr=0.3,0.1

Type RM Length L Ch R = 1 ,24000   ,225.6,208,178.5
XS GIS Cut Line= 4
1989598.25154803174329.6705802671989736.41419065174284.886768567
 1989982.9119444174257.9441942881990066.12185093 174212.26403635
#Sta/Elev= 30
       0 1714.08    26.7 1697.11    46.6 1683.33    70.5 1666.21   101.8 1642.41
   143.9 1613.15   146.6 1612.13   156.5 1611.27   166.4 1609.42   197.2 1608.99
   219.2 1609.46   232.4 1607.49   248.9 1607.87   255.5 1606.44   258.8 1606.21
   276.2 1607.48   281.9 1609.03     305 1608.42     338 1608.72   351.2 1607.72
   354.5 1608.32   364.4 1616.76   367.7 1618.91   387.5 1629.42     398 1632.26
   413.3 1638.74   426.3 1642.34   453.9 1652.57   469.1 1659.26   488.1 1669.04
#Mann= 6 ,-1 , 0
       0      .1       0  175.24     .04       0  185.24    .035       0
   255.5    .045       0   276.2    .035       0  365.24      .1       0
Bank Sta=255.5,276.2
XS Rating Curve= 0 ,0
Exp/Cntr=0.3,0.1

Type RM Length L Ch R = 1 ,23792   ,157.3,184.3,216.8
XS GIS Cut Line= 4
 1989758.5375974174564.8329539891989935.91989507174470.374215059
1989983.17526594174365.7222932331990093.34915015174325.172256602
#Sta/Elev= 30
       0 1654.22    17.4 1646.82    37.6 1637.31    58.4 1628.91    73.1 1623.62
    93.5 1615.37    99.1 1612.63   102.8 1611.51   125.1 1609.52   158.6 1607.67
   235.5 1607.67   238.7 1607.24   242.7  1605.9   246.1 1605.45   260.7    1605
   270.9 1605.54   285.5 1606.72   308.1 1606.06   309.4 1606.63   311.1  1608.1
   315.8 1613.04   320.6  1618.7     334 1627.76   344.5 1631.29   351.4 1635.34
   358.4 1638.54   365.4 1640.49   410.9 1656.91   421.4 1661.54   433.2 1667.87
#Mann= 4 ,-1 , 0
       0     .04       0     110    .035       0   242.7    .045       0
   270.9      .1       0
Bank Sta=242.7,270.9
XS Rating Curve= 0 ,0
Exp/Cntr=0.3,0.1

Type RM Length L Ch R = 1 ,23608   ,234.5,207.8,180.6
XS GIS Cut Line= 4
1989765.34479948 174634.606775281989917.65594595174559.727552431
1990120.77973194174597.1883018171990242.69984514174472.935725948
#Sta/Elev= 30
       0 1660.32     9.5 1654.49    34.9 1641.12    56.9 1633.39    75.3  1628.3
    97.2 1621.29   115.5 1617.45   130.1 1613.71   135.4 1612.88   190.4 1607.71
   206.6  1606.8   243.7 1606.16     267 1604.19     277 1603.54   283.7  1603.9
   287.1 1605.02   290.4 1605.83   297.1 1606.28   367.1 1606.75   376.3 1607.79
   386.6 1610.33   405.3 1616.42   423.9 1624.58   438.4 1632.75   458.7 1645.92
   480.5 1660.83   485.2 1663.57   494.6 1667.81   506.1 1676.01   550.3  1704.2
#Mann= 6 ,-1 , 0
       0      .1       0     110     .04       0     140    .035       0
  209.72      .1       0     267    .045       0   287.1      .1       0
Bank Sta=267,287.1
XS Rating Curve= 0 ,0
Exp/Cntr=0.3,0.1

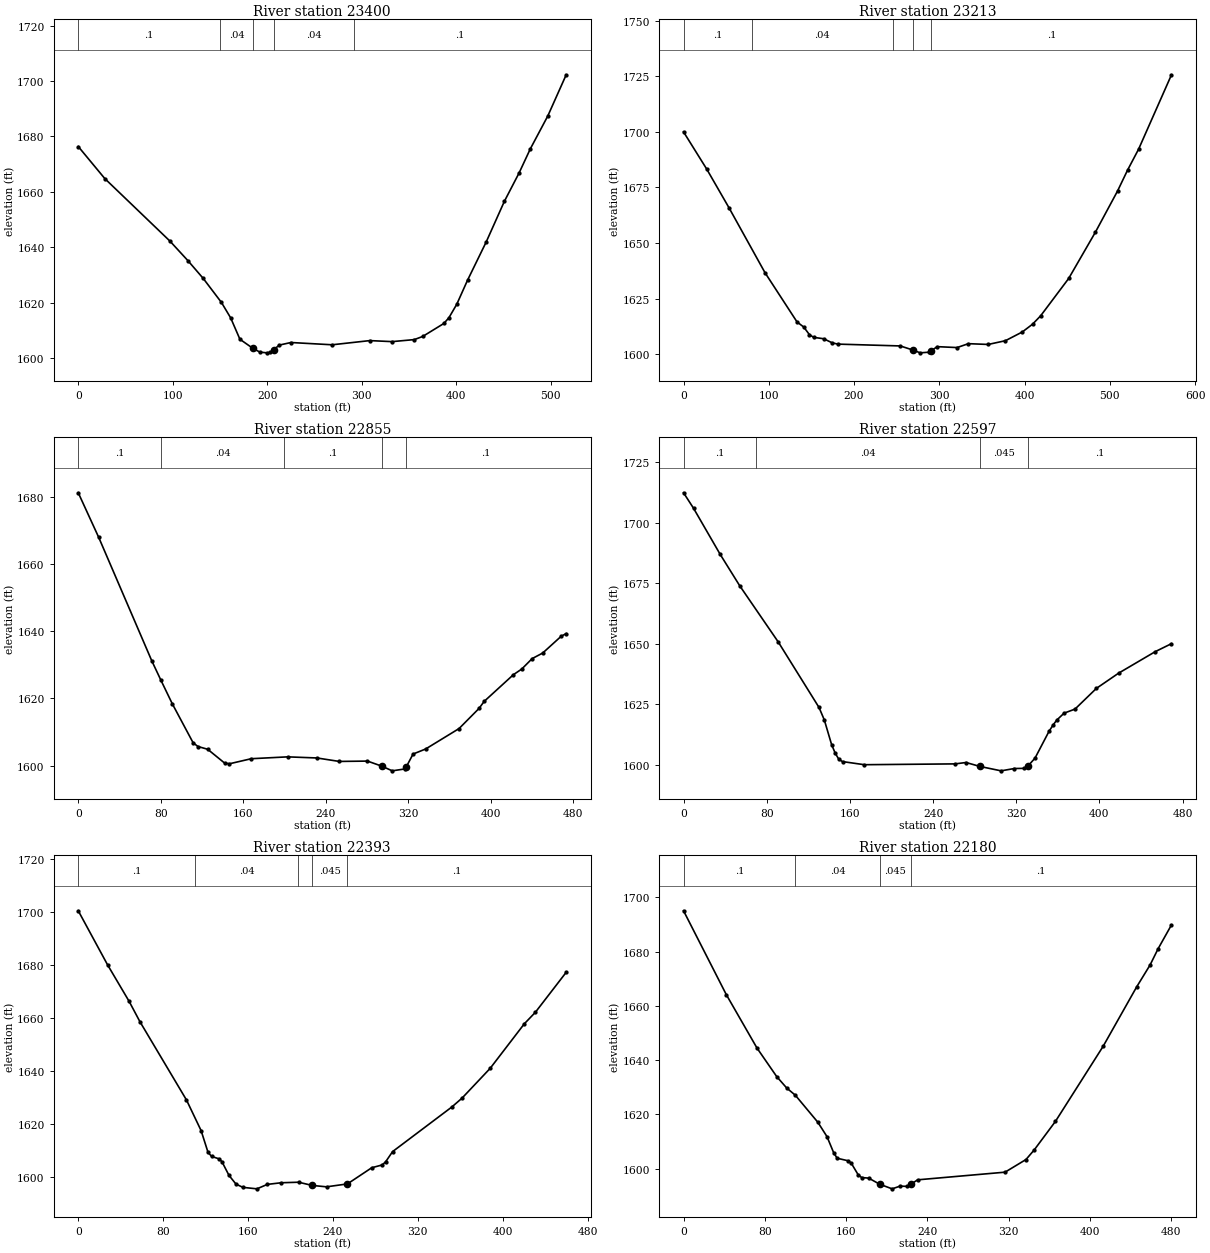
Type RM Length L Ch R = 1 ,23400   ,193,187.1,181.3
XS GIS Cut Line= 4
 1989926.9113771174875.1762992091990056.73300812174797.305869699
1990124.54695019174655.9972784951990269.97689949174506.956164859
#Sta/Elev= 30
       0 1676.38    28.1  1664.8      97 1642.23   116.1 1635.14   132.3 1628.72
   151.5 1620.08   161.3 1614.49   171.1 1606.76     185 1603.44   192.3 1602.12
   199.6 1601.86   203.2    1602   206.9 1603.06   212.9 1604.67   225.1 1605.59
   268.7 1604.77   308.6 1606.28   332.1 1605.91   355.6 1606.64   364.5 1607.77
   386.9 1612.46   392.3 1614.55   400.6 1619.41     412  1628.1   431.8 1641.95
     451  1656.6   466.6 1666.87   478.5 1675.58   496.9 1687.39   516.4 1702.29
#Mann= 5 ,-1 , 0
       0      .1       0     150     .04       0     185    .045       0
   206.9     .04       0  291.39      .1       0
Bank Sta=185,206.9
XS Rating Curve= 0 ,0
Exp/Cntr=0.3,0.1

Type RM Length L Ch R = 1 ,23213   ,339.6,358.1,372
XS GIS Cut Line= 4
1990120.52051922175010.3812592681990231.88095193174933.112282423
1990276.39545842174673.207117406 1990370.4160232174527.845506761
#Sta/Elev= 30
       0 1699.94    27.2 1683.22    53.3 1665.86    95.5  1636.7   133.1 1614.55
     141 1612.25   147.7  1608.8   152.7 1607.61   164.3    1607   174.3 1605.16
     181 1604.58   254.2 1603.76   269.1 1601.91   277.5 1600.66   287.5 1600.94
   290.8  1601.7   297.6 1603.44   320.8 1603.03   334.1 1604.78   357.3 1604.43
   377.5 1606.11   397.3 1610.03   409.3 1613.52   418.8 1617.28   451.7 1634.07
   482.9 1654.77     509 1673.35   520.8 1682.78   533.7 1692.16   572.3 1725.61
#Mann= 5 ,-1 , 0
       0      .1       0      80     .04       0  245.54      .1       0
   269.1    .045       0   290.8      .1       0
Bank Sta=269.1,290.8
XS Rating Curve= 0 ,0
Exp/Cntr=0.3,0.1

Type RM Length L Ch R = 1 ,22855   ,251,258.3,267
XS GIS Cut Line= 2
1990285.33559217175119.0486628221990668.24070901174841.087911339
#Sta/Elev= 30
       0 1681.21    19.8 1667.97    71.4 1631.14      80 1625.54    91.1 1618.48
   111.4 1606.82   116.1 1605.71   125.5 1604.89   141.9 1600.79   146.6 1600.57
   167.8 1602.08   203.1 1602.63   231.5  1602.3   253.1 1601.27   280.5 1601.37
   294.6 1599.84   304.5 1598.47   316.6 1599.03   318.1 1599.64   324.7 1603.47
   336.9 1604.97   369.3 1611.05   388.6 1617.02   393.7 1619.15     422 1627.08
   430.1 1628.76   440.2 1631.87   450.4 1633.52   468.4 1638.53   473.2 1639.31
#Mann= 5 ,-1 , 0
       0      .1       0      80     .04       0     200      .1       0
   294.6    .045       0   318.1      .1       0
Bank Sta=294.6,318.1
XS Rating Curve= 0 ,0
Exp/Cntr(USF)=0,0
Exp/Cntr=0.3,0.1

Type RM Length L Ch R = 1 ,22597   ,193.7,204,215.6
XS GIS Cut Line= 3
1990390.06987343175301.4504052151990494.16857706175222.949723054
 1990812.4771081175106.645185765
#Sta/Elev= 30
       0 1712.32     9.6 1705.94    35.3 1686.86      54 1673.96    91.1 1650.74
   130.3 1623.72   135.4 1618.56   142.4  1608.4   145.9 1604.82   149.4  1602.3
   152.9 1601.38   173.9 1600.09   261.2 1600.43   271.7    1601     285 1599.38
   305.4 1597.56   318.2 1598.52   327.5 1598.58     331 1599.43     331 1599.44
     338 1602.77   351.5 1613.86   355.5 1616.52     359 1618.52     366 1621.37
   376.5 1623.04   397.1  1631.6   418.4 1637.86   453.8 1646.78   469.3 1650.05
#Mann= 4 ,-1 , 0
       0      .1       0      70     .04       0     285    .045       0
     331      .1       0
Bank Sta=285,331
XS Rating Curve= 0 ,0
Exp/Cntr=0.3,0.1

Type RM Length L Ch R = 1 ,22393   ,214.5,212.5,199.2
XS GIS Cut Line= 3
1990445.74488267175395.0931341651990569.12406441175364.885043887
1990901.99669557175363.444036825
#Sta/Elev= 30
       0 1700.51    27.7 1680.03      48 1666.24    58.1 1658.61     102 1629.01
   115.8 1617.42   122.3 1609.23   125.7 1607.67   133.1 1606.71   135.6 1605.55
   142.1 1600.49   148.7  1597.2   155.2 1595.98   168.4 1595.42   178.2  1597.1
   191.3 1597.72   207.7 1597.92   220.5 1596.71     234 1596.18   253.7 1597.28
   276.6 1603.39   286.5 1604.46   289.8 1605.69   296.3  1609.5   352.1 1626.35
   361.7 1629.69   388.2 1640.94   420.5 1657.83   430.8 1662.12   459.9 1677.26
#Mann= 5 ,-1 , 0
       0      .1       0     110     .04       0  207.02      .1       0
   220.5    .045       0   253.7      .1       0
Bank Sta=220.5,253.7
XS Rating Curve= 0 ,0
Exp/Cntr=0.3,0.1

Type RM Length L Ch R = 1 ,22180   ,202.7,201.7,200.9
XS GIS Cut Line= 4
1990440.64877424175549.6993871271990589.01776076175567.028226261
1990765.88176237175510.9361530771990910.39194807175495.787992211
#Sta/Elev= 30
       0 1695.03    42.1 1664.13    72.3 1644.45    91.7 1633.94   101.6 1629.71
     110 1627.09   132.2 1617.11   141.2 1611.81   147.8 1605.85   151.2 1603.86
   161.6 1602.96     165 1602.08   171.9 1597.75   175.3 1596.75   182.2 1596.54
   193.1 1594.28   205.3 1592.59   213.1 1593.59   220.1 1593.49   223.4 1594.22
   230.4 1595.91   316.4 1598.73     337 1603.39   345.1 1606.92     366 1617.44
   412.9 1645.08   445.9 1666.97   459.1 1675.04   467.1 1681.09   480.2 1689.83
#Mann= 4 ,-1 , 0
       0      .1       0     110     .04       0   193.1    .045       0
   223.4      .1       0
Bank Sta=193.1,223.4
XS Rating Curve= 0 ,0
Exp/Cntr=0.3,0.1

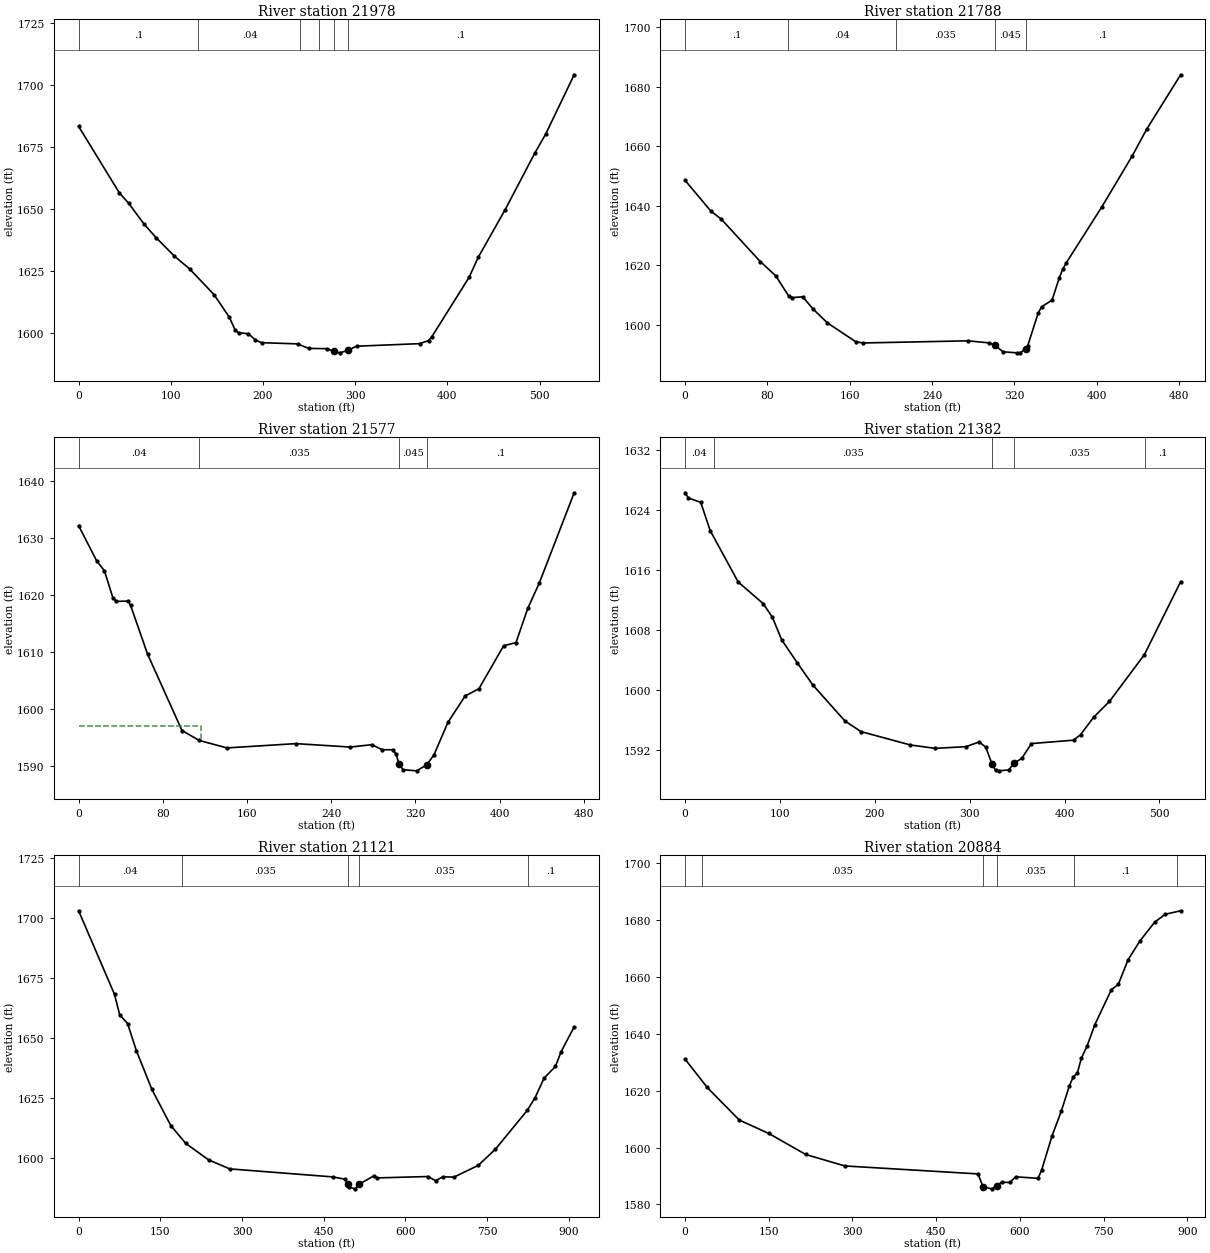
Type RM Length L Ch R = 1 ,21978   ,187.1,190.9,192.8
XS GIS Cut Line= 4
1990415.58748108  175767.85319771990584.67407938175789.406568249
1990785.73610177175705.697768061 1990932.7603954175680.061031157
#Sta/Elev= 30
       0 1683.39    44.3 1656.53    54.2 1652.48    70.8 1644.12      84  1638.6
   103.6 1631.24   120.4 1625.99   146.8 1615.69   163.4 1606.58     170 1601.21
   173.5 1600.33   184.2 1599.88   191.8 1597.38   198.4 1596.31   237.5 1595.81
   249.5    1594   269.5 1593.88   276.6 1592.75   283.7 1592.21   292.2 1593.25
   301.5 1594.88   369.9 1595.91   379.6 1597.15   383.2 1598.74   423.5 1622.61
   433.5 1630.71   462.7  1649.9   494.9 1672.69   506.5 1680.22   537.5 1704.17
#Mann= 6 ,-1 , 0
       0      .1       0     130     .04       0  240.45    .035       0
  260.45      .1       0   276.6    .045       0   292.2      .1       0
Bank Sta=276.6,292.2
XS Rating Curve= 0 ,0
Exp/Cntr=0.3,0.1

Type RM Length L Ch R = 1 ,21788   ,200.9,210.3,215.6
XS GIS Cut Line= 3
1990448.95314169175923.7327503711990586.87755961175966.955662596
1990911.10293769175875.620630563
#Sta/Elev= 30
       0 1648.51    24.9 1638.26    35.2 1635.49      73 1621.27    88.1 1616.47
   100.5 1609.77   103.9 1609.17   114.3 1609.43   124.6 1605.23   138.3 1600.68
   165.6 1594.39   172.5 1593.94   274.7 1594.66   295.2 1593.98     3011593.203
   308.8 1590.99   322.4 1590.63   325.8  1590.7   330.91592.005   332.7 1592.86
   342.9 1603.87   346.3 1606.08   356.5 1608.32   363.3 1615.61   366.7 1618.62
   370.1 1620.73     405 1639.71   434.3 1656.68   448.5 1665.75   481.4 1683.96
#Mann= 5 ,-1 , 0
       0      .1       0     100     .04       0  204.54    .035       0
     301    .045       0   330.9      .1       0
Bank Sta=301,330.9
XS Rating Curve= 0 ,0
Exp/Cntr=0.3,0.1

Type RM Length L Ch R = 1 ,21577   ,202.2,195.1,188
XS GIS Cut Line= 4
1990447.80680606176079.8552340921990528.55167571176123.425423599
1990819.95177295176127.7233062891990886.87314134176070.964935255
#Sta/Elev= 30
       0 1632.13    17.1 1625.97    24.5 1624.22    32.5 1619.52    35.7 1618.85
    46.9 1618.91    49.4 1618.14    65.5 1609.61    98.2 1596.21   114.6 1594.47
   140.9 1593.16   206.5 1593.91   258.3 1593.31   278.7 1593.73   288.5 1592.84
   298.4 1592.84   301.6 1592.07   304.51590.397   308.2 1589.34   321.3 1589.14
   330.81590.201   337.7 1591.95   350.9 1597.63   367.3 1602.27   380.4 1603.54
   403.9 1611.08   415.6 1611.62   426.8 1617.63   437.8 1622.09   470.9  1637.9
#Mann= 4 ,-1 , 0
       0     .04       0   114.6    .035       0   304.5    .045       0
   330.8      .1       0
#XS Ineff= 2 , 0
             116    1597
Permanent Ineff=
       F       F
Bank Sta=304.5,330.8
XS Rating Curve= 0 ,0
Exp/Cntr=0.3,0.1

Type RM Length L Ch R = 1 ,21382   ,277.8,261.3,238.3
XS GIS Cut Line= 4
1990423.32372576176374.7130768951990569.87111218176376.361070052
1990843.53587714176287.7340852661990883.85214077176209.449222139
#Sta/Elev= 30
       0 1626.28     3.4  1625.6    16.5    1625    26.4 1621.26    55.9 1614.42
    82.2 1611.54      92 1609.73   101.8 1606.71   118.3 1603.64   134.7 1600.69
   168.5 1595.91   185.4  1594.5   237.5 1592.72   263.6 1592.27   296.1  1592.5
   309.9 1593.12   316.8 1592.45   323.5  1590.2   327.2 1589.36   330.6 1589.28
     341  1589.4   347.11590.318   354.8 1590.94   365.1 1592.91   409.4 1593.36
   416.8 1594.09   430.6 1596.41   447.3 1598.52   484.2 1604.76   522.3 1614.45
#Mann= 5 ,-1 , 0
       0     .04       0      30    .035       0   323.5    .045       0
   347.1    .035       0  484.21      .1       0
Bank Sta=323.5,347.1
XS Rating Curve= 0 ,0
Exp/Cntr=0.3,0.1

Type RM Length L Ch R = 1 ,21121   ,250.5,237,221.2
XS GIS Cut Line= 4
1990582.68879905176988.1497725691990734.66028575 176796.14278668
1990889.19964703176298.6754469511990953.16306848176169.231223639
#Sta/Elev= 30
       0 1702.91    65.9 1668.12    75.4 1659.65    89.9 1656.01   106.2 1644.64
   134.6 1628.59   169.3 1613.57   196.7 1606.17   238.6 1599.32   277.5 1595.56
   466.4 1592.23   489.8 1591.24   493.9 1589.21   497.4 1587.89   507.7 1587.26
   515.7 1589.24     542 1592.63   548.9 1591.81   641.7 1592.38   655.7 1590.64
   669.1 1592.26   689.5 1592.15   734.1 1597.02   765.6 1603.77   823.9 1619.86
   838.5 1625.23     855 1633.33   875.8 1638.16   886.1 1644.25   910.2 1654.61
#Mann= 5 ,-1 , 0
       0     .04       0     190    .035       0   493.9    .045       0
   515.7    .035       0  825.79      .1       0
Bank Sta=493.9,515.7
XS Rating Curve= 0 ,0
Exp/Cntr(USF)=0,0
Exp/Cntr=0.3,0.1

Type RM Length L Ch R = 1 ,20884   ,109,104.8,101.3
XS GIS Cut Line= 4
1991349.81155214176893.7289228731991163.75670099176783.549488316
1990974.59252906 176335.885657651991040.16642718176161.892988512
#Sta/Elev= 30
       0 1631.05    39.7  1621.1    97.2 1609.63   149.9 1604.95   216.2 1597.55
   286.2 1593.52   524.9 1590.72   534.11586.151   549.8 1585.47   558.61586.629
   567.2 1587.74   581.9 1587.74   592.5 1589.69   632.6 1589.18   638.9 1591.97
   657.6 1604.02   674.5  1612.9   688.7 1621.64   695.8 1624.83     703 1626.13
   710.4 1631.46   720.5 1635.65   734.5 1643.23   763.9 1655.42   776.6 1657.41
   794.1 1666.05   815.1 1672.57   841.9 1679.27   860.7 1681.99   888.2 1683.22
#Mann= 6 ,-1 , 0
       0     .04       0      30    .035       0   534.1    .045       0
   558.6    .035       0  696.23      .1       0  882.22    .035       0
Bank Sta=534.1,558.6
XS Rating Curve= 0 ,0
Exp/Cntr=0.3,0.1

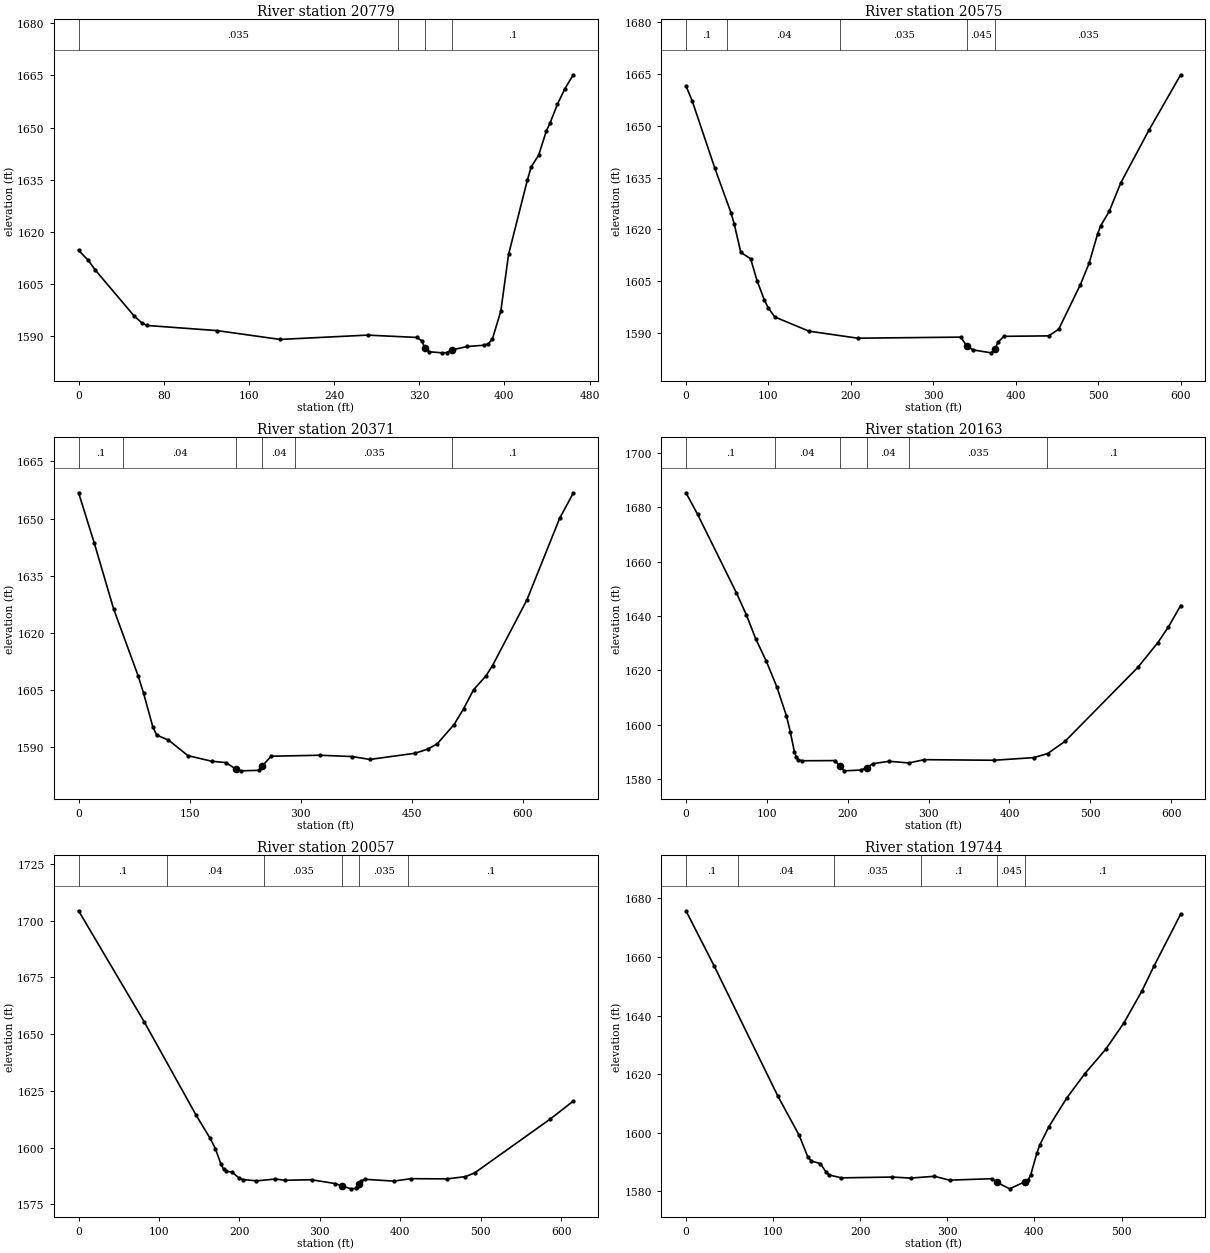
Type RM Length L Ch R = 1 ,20779   ,201.2,204.3,205.7
XS GIS Cut Line= 3
1991301.41550833176697.1898043561991083.71727241176362.546296349
1991059.47536781 176301.68570264
#Sta/Elev= 30
       0 1614.68     9.1 1611.79    15.7 1608.99      52 1595.85    59.1 1593.88
    63.9 1593.06   130.3 1591.56   189.2 1589.03   271.4 1590.27   317.6  1589.6
   322.3 1588.68   325.31586.586   329.5 1585.47   341.8 1585.17   345.7 1585.24
   350.8 1586.02   365.3 1587.01     381 1587.36   384.9 1587.79   388.7 1589.15
   396.6 1597.19   403.9 1613.51   421.6 1634.96   425.1 1638.65   432.2 1642.11
   439.3 1648.97   442.8 1651.26   449.8 1656.74   456.9 1661.25   464.7  1665.2
#Mann= 4 ,-1 , 0
       0    .035       0     300      .1       0   325.3    .045       0
   350.8      .1       0
Bank Sta=325.3,350.8
XS Rating Curve= 0 ,0
Exp/Cntr=0.3,0.1

Type RM Length L Ch R = 1 ,20575   ,196.9,203.4,209.3
XS GIS Cut Line= 4
1991482.58596155176572.6701554931991401.88857382 176518.41919222
1991229.95523409176209.3755467821991090.69907349176156.145973476
#Sta/Elev= 30
       0 1661.63     7.6 1657.22    34.9 1637.82    54.6  1624.8    58.6 1621.47
    66.5  1613.3    78.4 1611.47    86.3 1605.05      95 1599.56    99.8 1597.18
   107.9 1594.56   149.2 1590.46   208.4 1588.42   333.2 1588.73   341.1 1586.04
   348.5 1585.01     370 1584.17   374.8 1585.16   378.2 1587.23   385.7 1588.96
     440 1589.09   452.1 1591.04   478.4 1603.97   488.9 1610.14   499.4 1618.77
   502.9 1620.97   513.5 1625.32   527.5 1633.55   561.3 1648.68     600 1664.83
#Mann= 5 ,-1 , 0
       0      .1       0      50     .04       0  187.24    .035       0
   341.1    .045       0   374.8    .035       0
Bank Sta=341.1,374.8
XS Rating Curve= 0 ,0
Exp/Cntr=0.3,0.1

Type RM Length L Ch R = 1 ,20371   ,224.6,208,190.1
XS GIS Cut Line= 4
1991575.80371605176393.5271102151991498.76747855176342.169618549
1991390.21641662175965.1589410941991272.58144981175824.441297725
#Sta/Elev= 30
       0 1656.77    21.3 1643.51    47.3 1626.32    80.5  1608.7    87.7 1604.24
   100.2  1595.4   105.5 1593.18   121.4 1591.88   147.6 1587.81   179.7 1586.33
   198.8 1585.98   212.5 1584.27   219.3 1583.81   243.2 1583.94   247.8 1585.04
   260.3 1587.65   325.5  1587.9   369.6 1587.56   393.5  1586.8   454.9 1588.44
     472 1589.54   484.6 1590.93   507.2 1595.95     520 1600.06   533.5 1605.08
     550 1608.64   559.2 1611.44   605.6 1628.65     650 1650.14   668.3  1656.7
#Mann= 6 ,-1 , 0
       0      .1       0      60     .04       0   212.5    .045       0
   247.8     .04       0  292.59    .035       0  504.91      .1       0
Bank Sta=212.5,247.8
XS Rating Curve= 0 ,0
Exp/Cntr=0.3,0.1

Type RM Length L Ch R = 1 ,20163   ,110.2,106.7,104.7
XS GIS Cut Line= 4
1991743.32346648176245.521819321 1991679.6859151176136.739651886
1991415.10226913175944.6483878821991340.04976421175804.839160604
#Sta/Elev= 30
       0 1685.39    14.3  1677.5    62.3 1648.58    74.8 1640.36    86.2 1631.64
    99.4 1623.34   112.4 1613.85   124.2 1603.25   128.9 1597.46     134 1590.07
   136.4 1588.03   138.7 1587.12   143.4  1586.7   184.7 1586.75     1901584.634
   195.9 1582.98   216.2 1583.27   223.41584.062     231 1585.61   251.3  1586.5
   275.6 1585.88   294.6 1587.09     381 1586.88     430 1587.85   447.2 1589.35
   468.6 1593.82   558.8  1621.1   583.2  1630.1   596.5 1635.96   611.7 1643.86
#Mann= 6 ,-1 , 0
       0      .1       0     110     .04       0     190    .045       0
   223.4     .04       0  276.03    .035       0  446.03      .1       0
Bank Sta=190,223.4
XS Rating Curve= 0 ,0
Exp/Cntr=0.3,0.1

Type RM Length L Ch R = 1 ,20057   ,279,312.7,343.2
XS GIS Cut Line= 4
1991824.91901667 176253.144938071991775.11761041176069.868122156
1991526.78065583 175907.965370831991497.52690473175782.632102081
#Sta/Elev= 30
       0 1704.37    81.6 1655.44   146.2 1614.26   163.5 1604.15     170 1599.62
   176.8  1592.9   180.2 1590.57   183.6 1589.59   190.7 1589.26   199.7 1586.55
   204.4 1585.96     221 1585.37   244.7 1586.16   256.5 1585.63   289.6 1585.85
   319.1 1584.18   326.9 1583.19   338.7 1581.85   344.3 1582.07   346.7 1582.69
     349 1584.19   351.4 1585.33   356.1 1586.05   391.7 1585.26   413.4 1586.32
   458.4 1586.25   480.9 1587.22   492.4 1588.86   586.7 1612.67   615.1 1620.54
#Mann= 6 ,-1 , 0
       0      .1       0     110     .04       0  229.92    .035       0
   326.9    .045       0     349    .035       0  409.92      .1       0
Bank Sta=326.9,349
XS Rating Curve= 0 ,0
Exp/Cntr=0.3,0.1

Type RM Length L Ch R = 1 ,19744   ,170.4,170.1,169.4
XS GIS Cut Line= 3
1991857.30521231176204.9995450791991810.53037121176073.607359655
1991943.47666775175666.351716858
#Sta/Elev= 30
       0 1675.76    32.4 1656.92   105.6 1612.46     130 1599.14   139.7 1591.89
   143.8 1590.39   154.2 1589.51   161.1  1586.5   164.5 1585.62   178.4 1584.64
     237 1584.91   257.8 1584.56   285.3 1585.17   302.6 1583.85   350.9 1584.35
   356.61583.154   371.6 1580.89   389.61583.381   393.1 1584.05   395.8  1585.7
   402.7 1592.96   406.1 1595.79   416.5 1602.04   437.3 1611.96   457.9 1620.19
   482.1  1628.6   502.8 1637.53   523.5 1648.47   537.3 1656.91   567.9 1674.62
#Mann= 6 ,-1 , 0
       0      .1       0      60     .04       0  169.47    .035       0
  269.47      .1       0   356.6    .045       0   389.6      .1       0
Bank Sta=356.6,389.6
XS Rating Curve= 0 ,0
Exp/Cntr=0.3,0.1