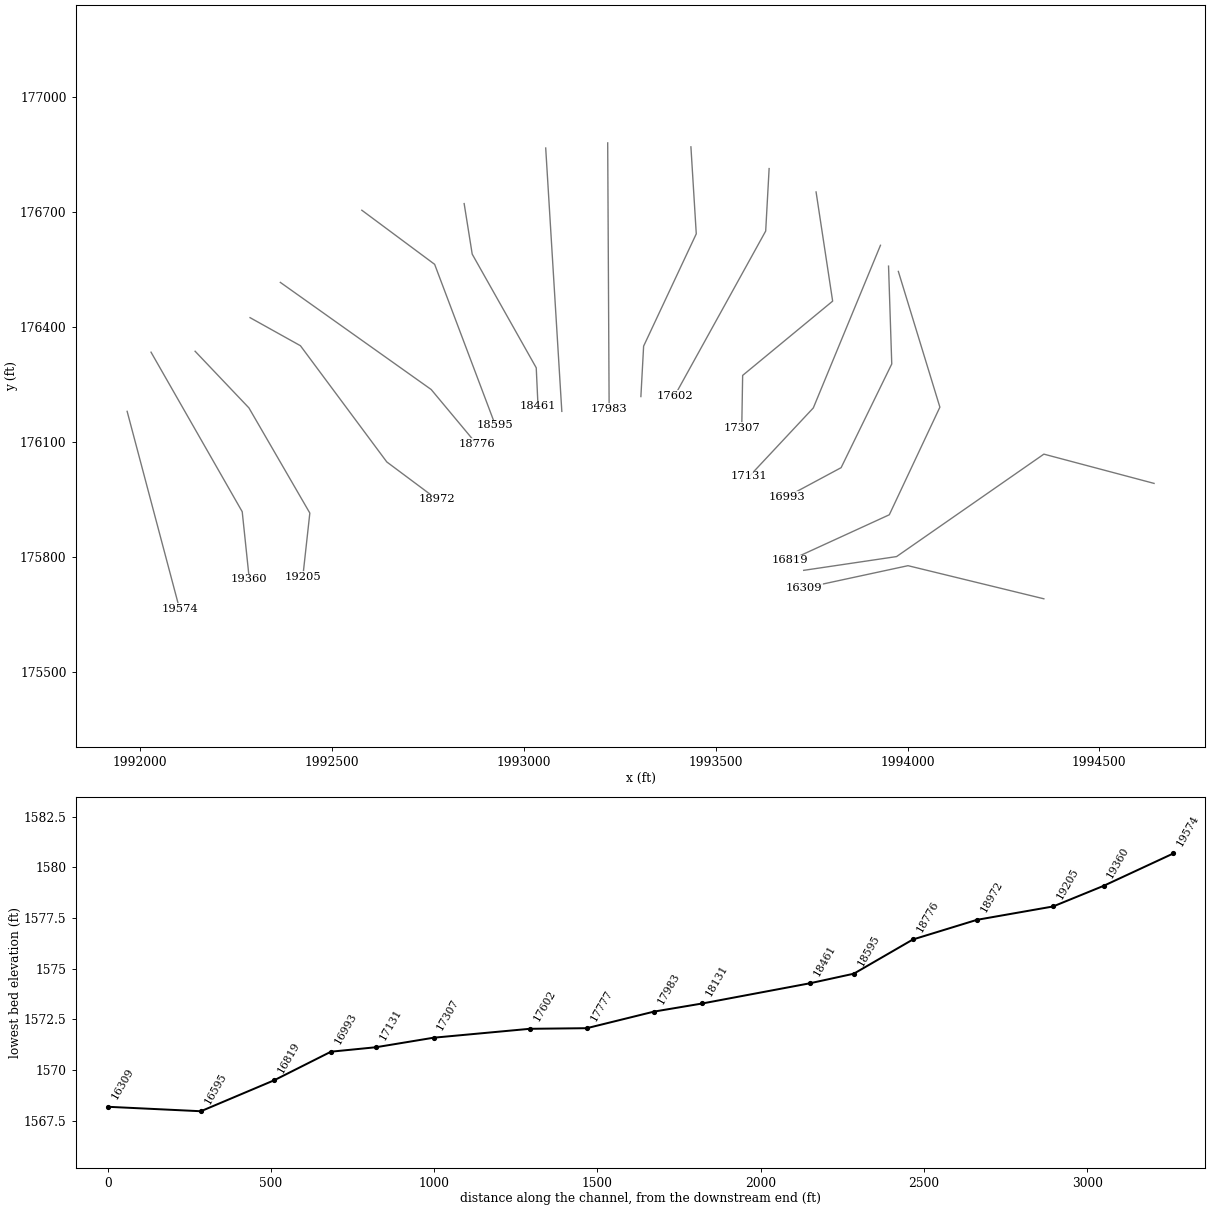
HEC-RAS study LICKCK.prj: LICKCK

--- LICKCK.g01 (geometry) --- (continued)

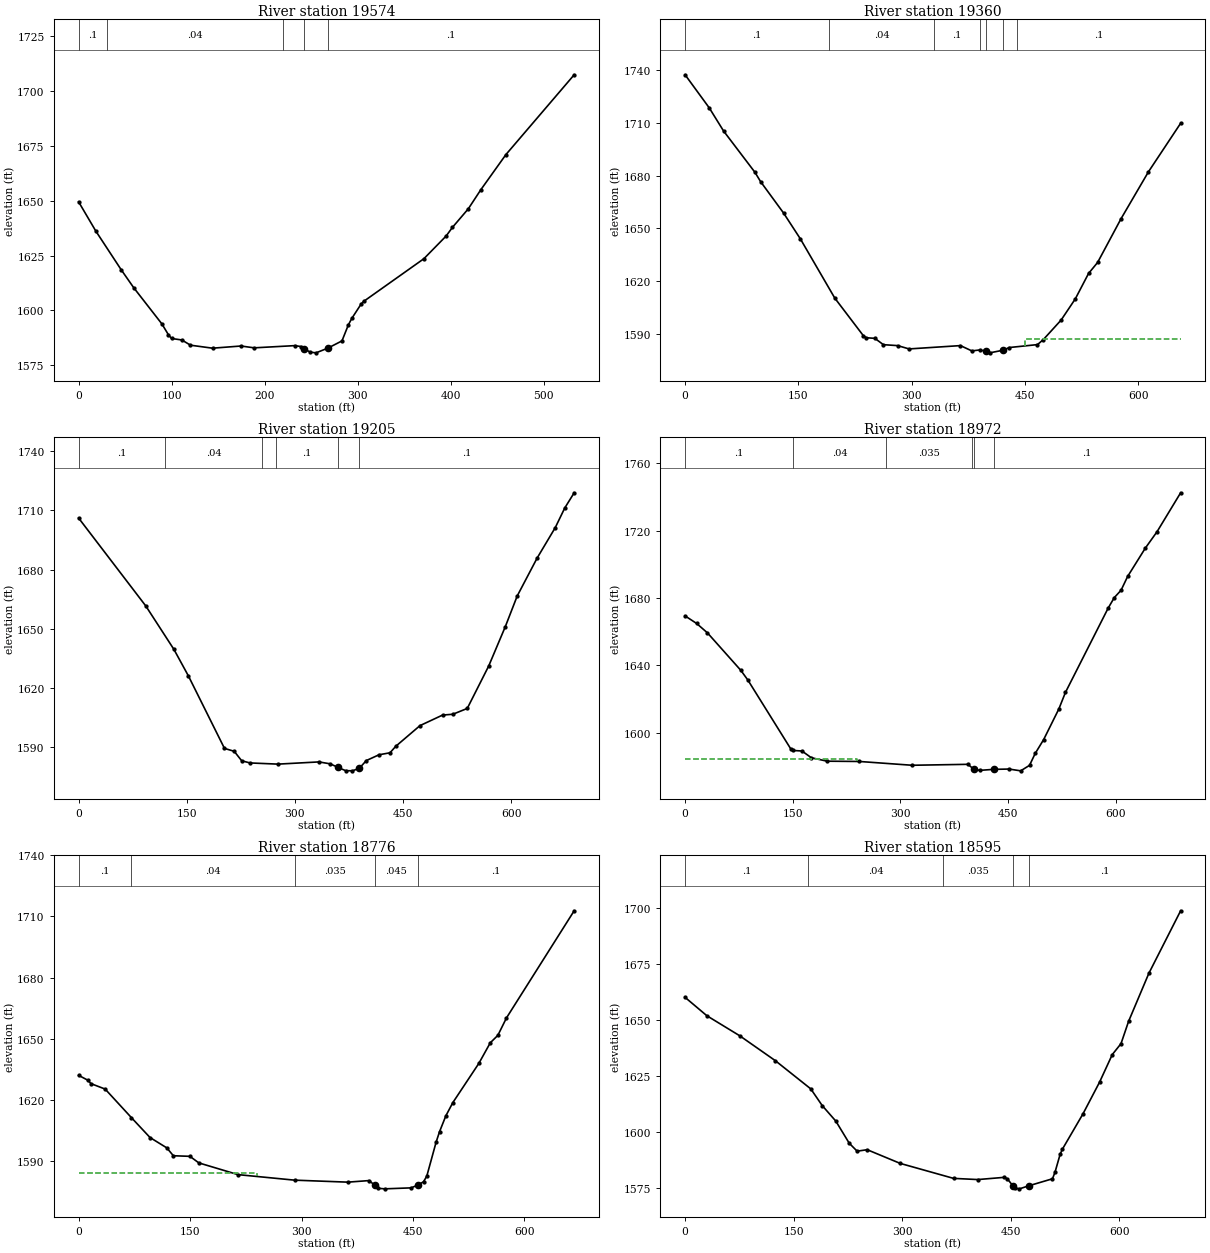
Type RM Length L Ch R = 1 ,19574   ,209.4,213.7,219.6
XS GIS Cut Line= 2
1991965.61870398176179.1495168511992102.21800563175664.017285419
#Sta/Elev= 30
       0 1649.46    18.5 1636.14    45.6 1618.64    59.2 1610.38    89.6 1593.83
    96.5 1588.97    99.9 1587.23     111 1586.55   120.3 1584.17     144 1582.81
   174.6  1583.8   188.8 1582.97   232.3 1583.97   239.1 1583.57   242.5 1582.47
   249.3 1580.99   255.3 1580.69   268.1 1582.85   283.2 1586.13     290 1593.35
   293.7 1596.34   303.6 1602.79   306.5 1604.12   371.3 1623.57   395.2  1633.9
     402 1637.85     419 1646.27   432.5 1654.98   459.5    1671   532.9 1707.35
#Mann= 5 ,-1 , 0
       0      .1       0      30     .04       0     220      .1       0
   242.5    .045       0   268.1      .1       0
Bank Sta=242.5,268.1
XS Rating Curve= 0 ,0
Exp/Cntr=0.3,0.1

Type RM Length L Ch R = 1 ,19360   ,153,155,153.8
XS GIS Cut Line= 3
1992027.90050833176333.4771755691992265.62820638175917.303096588
1992284.04064375175741.570670641
#Sta/Elev= 30
       0 1737.43      32 1718.57    50.9 1705.44    92.5 1681.87     100 1676.55
   130.3 1658.74   152.6 1643.99   198.2 1610.23   236.1 1588.78   239.8 1587.69
   251.2 1587.34   262.5 1583.74   281.4  1583.2   296.5 1581.32   364.5 1583.21
   379.6 1580.19     390 1580.73   398.5 1580.01   403.3 1579.09   421.2  1580.6
   429.1 1582.11   466.5 1583.78   474.1 1586.58   497.8 1597.77   516.6 1609.85
   534.1 1624.29   546.1 1630.57     577 1655.39   613.3 1682.12     656 1709.81
#Mann= 7 ,-1 , 0
       0      .1       0     190     .04       0     330      .1       0
     390    .035       0   398.5    .045       0   421.2    .035       0
     440      .1       0
#XS Ineff= 2 , 0
                             450          1587.2
Permanent Ineff=
       F       F
Bank Sta=398.5,421.2
XS Rating Curve= 0 ,0
Exp/Cntr=0.3,0.1

Type RM Length L Ch R = 1 ,19205   ,229.5,233.3,234.9
XS GIS Cut Line= 4
1992142.79088125  176335.91284111992283.13644218176188.097143552
1992441.87778005175913.8014494291992423.65974072175748.184864582
#Sta/Elev= 30
       0  1706.1    93.2 1661.56   132.2 1639.57   152.2  1626.2   202.3 1589.44
   215.8 1587.96   226.2 1583.17   237.7 1582.07   276.5 1581.47   333.3 1582.59
     349 1581.62   359.9  1579.8   370.3 1578.17   379.9 1578.07   389.5 1579.42
   399.1 1583.28   416.7 1586.21   431.9 1587.21   439.9  1590.5   473.5 1600.97
   504.8 1606.31   519.1 1606.73   539.1 1609.68   568.8 1631.14   591.9 1651.12
   608.4 1666.65     636 1685.84   661.2 1701.29   674.4 1711.24   687.4 1718.91
#Mann= 6 ,-1 , 0
       0      .1       0     120     .04       0  253.83    .035       0
  273.83      .1       0   359.9    .045       0   389.5      .1       0
Bank Sta=359.9,389.5
XS Rating Curve= 0 ,0
Exp/Cntr=0.3,0.1

Type RM Length L Ch R = 1 ,18972   ,187.1,196.1,206.3
XS GIS Cut Line= 4
1992286.04588125176423.5415083341992417.36624994176350.340128587
1992642.55178598176047.1044096611992772.60806023175950.106613822
#Sta/Elev= 30
       0 1669.41    16.1 1664.92    31.1 1659.36    77.7 1637.06    87.5 1631.28
   147.5 1590.23     150 1589.52   162.8 1589.19   175.8  1585.2   197.8 1583.14
   242.8 1582.97   316.3 1580.72     394 1581.28   402.1 1578.39   410.3 1577.69
     4301578.294   451.2 1578.47   467.5 1577.41   479.8 1580.67   487.7 1587.74
   499.5 1595.99   520.6 1614.11   529.9 1624.05   589.4  1674.1   597.9  1680.3
   607.3 1684.65   616.5 1692.87   641.1 1709.67   657.5 1719.46   690.3 1742.54
#Mann= 6 ,-1 , 0
       0      .1       0     150     .04       0  280.34    .035       0
  400.34      .1       0   402.1    .045       0     430      .1       0
#XS Ineff= 2 , 0
             240  1584.5
Permanent Ineff=
       F       F
Bank Sta=402.1,430
XS Rating Curve= 0 ,0
Exp/Cntr=0.3,0.1

Type RM Length L Ch R = 1 ,18776   ,191,181.1,144.7
XS GIS Cut Line= 3
     1992365.016      176515.5241992758.23921742176236.097234092
1992876.40964375176094.282454922
#Sta/Elev= 30
       0  1632.1    12.2 1629.74    16.8    1628    35.7 1625.36      71 1611.37
    96.1  1601.6   118.7 1596.52   127.5 1592.67   149.8 1592.38   161.8 1589.16
   214.5 1583.41   290.6  1580.7   362.3 1579.72     391 1580.49   398.61578.182
   403.3 1576.69   412.2 1576.44   447.6 1576.92   456.9 1578.37   464.2 1579.91
   468.6 1582.64   481.2 1599.37   485.8 1604.48   494.3 1612.25   503.7 1618.74
   538.7 1637.96   554.1 1648.06   564.3 1651.72   575.9 1660.27     667 1712.79
#Mann= 5 ,-1 , 0
       0      .1       0      71     .04       0   290.6    .035       0
   398.6    .045       0   456.9      .1       0
#XS Ineff= 2 , 0
             240    1584
Permanent Ineff=
       F       F
Bank Sta=398.6,456.9
XS Rating Curve= 0 ,0
Exp/Cntr=0.3,0.1

Type RM Length L Ch R = 1 ,18595   ,130,133.7,136.9
XS GIS Cut Line= 3
     1992577.399      176703.7991992767.25487955176562.642613822
1992925.40750663176143.202474997
#Sta/Elev= 30
       0 1660.21    30.1 1652.01    75.5 1643.07   124.6 1631.98   173.7 1619.36
   189.5 1611.91   208.3 1604.98   226.8 1595.12   237.7 1591.57   251.7 1592.21
   297.3  1586.1     371 1579.42   404.5 1578.89   441.1 1579.88   445.2 1579.25
   452.8 1576.21   455.4 1575.15   462.1 1574.75   474.7 1576.09   507.7 1579.24
   511.2 1582.18   518.2 1590.09   521.2 1592.34   549.8 1608.19   572.7 1622.33
   590.3 1634.66   602.4 1639.56   612.9 1649.54   640.9 1670.96   684.8 1698.86
#Mann= 5 ,-1 , 0
       0      .1       0     170     .04       0  356.58    .035       0
   452.8    .045       0   474.7      .1       0
Bank Sta=452.8,474.7
XS Rating Curve= 0 ,0
Exp/Cntr=0.3,0.1

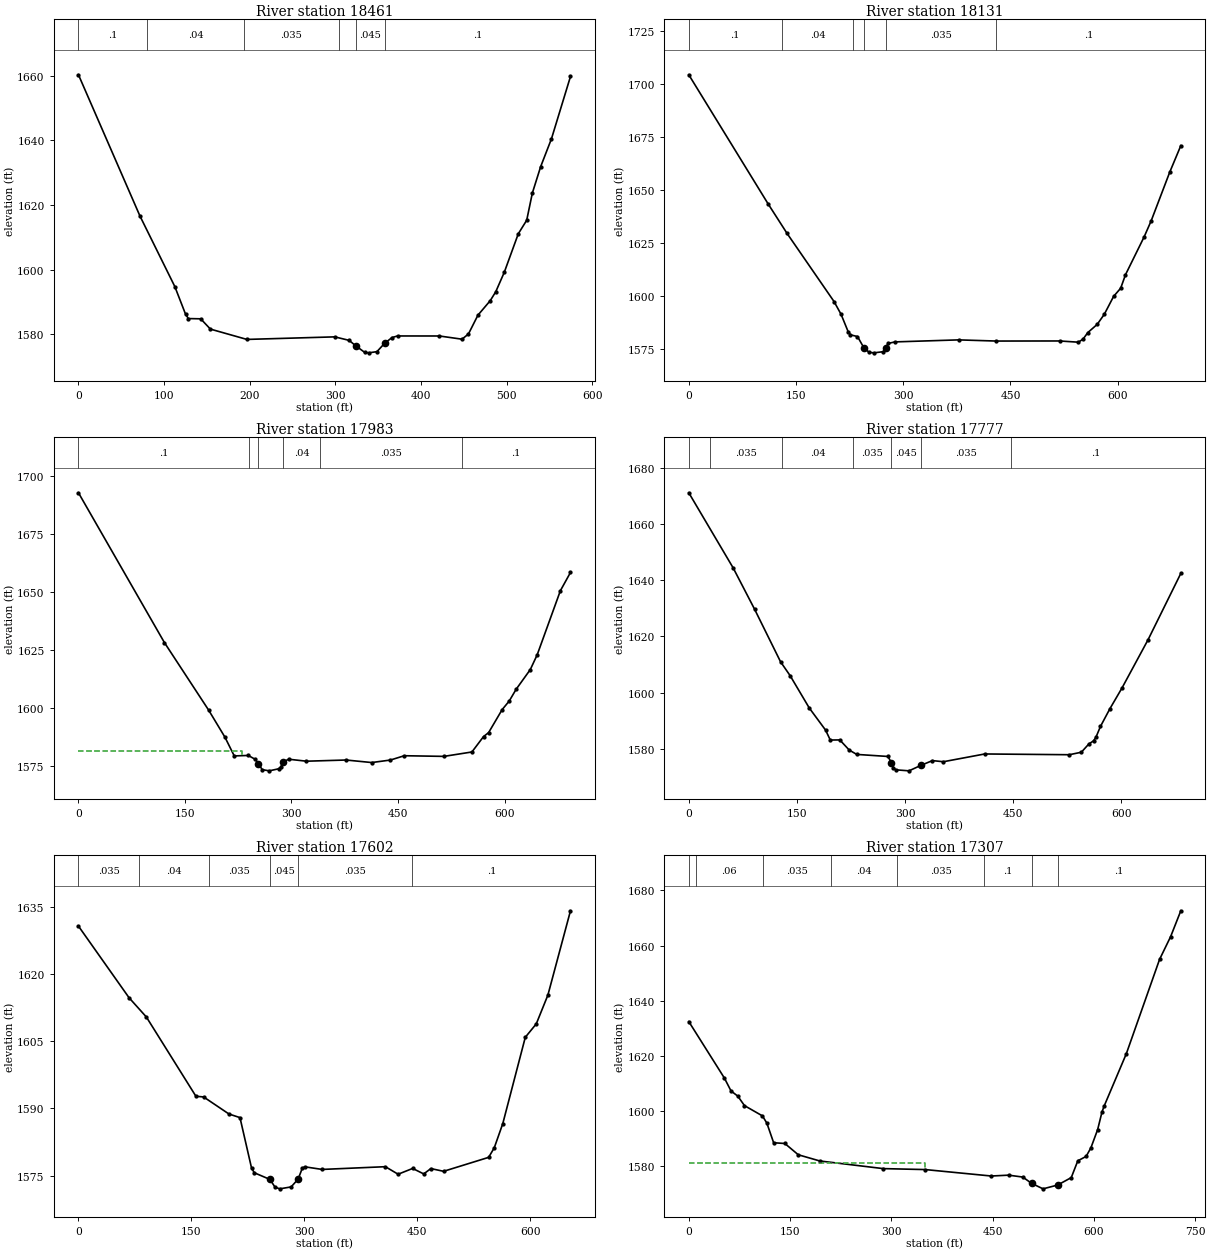
Type RM Length L Ch R = 1 ,18461   ,330.1,330.4,308
XS GIS Cut Line= 4
1992844.16914451176721.1136266461992865.17902746176589.218250322
1993032.09087538176292.7454575231993036.75973825 176192.36490563
#Sta/Elev= 30
       0 1660.27    71.8 1616.58   112.5 1594.76     125 1586.23   128.3 1584.88
   142.7  1584.8     154 1581.62   196.6 1578.43   299.2 1579.22   315.9 1578.14
   323.4 1576.51   333.9 1574.46   338.8 1574.28   348.4 1574.65   357.3 1577.21
     366 1579.01   372.4  1579.5   421.3 1579.49   447.7  1578.5   455.2 1580.11
   466.3 1585.94   480.6  1590.4   487.1 1593.18     497 1599.17   513.4 1611.11
   523.2 1615.28   529.8  1623.7   539.5 1631.86   552.1 1640.47   574.3 1659.74
#Mann= 6 ,-1 , 0
       0      .1       0      80     .04       0  193.56    .035       0
  303.56      .1       0   323.4    .045       0   357.3      .1       0
Bank Sta=323.4,357.3
XS Rating Curve= 0 ,0
Exp/Cntr(USF)=0,0
Exp/Cntr=0.3,0.1

Type RM Length L Ch R = 1 ,18131   ,148.7,147.6,145.9
XS GIS Cut Line= 2
 1993056.7591579176866.0797402831993098.77892381176179.056567683
#Sta/Elev= 30
       0  1704.4   111.1 1643.45   137.4 1629.63   203.2 1597.46     213 1591.47
   222.9 1583.28   226.2 1581.77     236 1580.97   245.3 1575.44   252.5 1573.49
   259.1 1573.28   272.2 1573.83   275.5 1575.68   278.8 1577.72   288.6 1578.44
   377.4 1579.39     430 1578.84   518.7 1578.88     545  1578.3   551.6 1579.77
   558.2 1582.83   571.3 1586.69   581.2 1591.42   594.3  1599.9   604.2 1603.77
   610.9 1610.11   637.1 1628.04   646.9 1635.58   672.7 1658.39   688.3 1670.98
#Mann= 6 ,-1 , 0
       0      .1       0     130     .04       0     230    .035       0
   245.3    .045       0   275.5    .035       0     430      .1       0
Bank Sta=245.3,275.5
XS Rating Curve= 0 ,0
Exp/Cntr(USF)=0,0
Exp/Cntr=0.3,0.1

Type RM Length L Ch R = 1 ,17983   ,217.8,206.1,191.7
XS GIS Cut Line= 2
1993218.37297659176879.4376905711993222.12750585176186.508897214
#Sta/Elev= 30
       0 1692.88     121 1628.26   183.3  1599.1   206.3  1587.4   219.4 1579.32
   239.1 1579.52     249 1577.84   253.3 1576.04   258.8 1573.39   268.7 1572.88
   281.8 1573.75   285.1  1574.6   288.3 1576.78   296.1 1577.89   321.1 1577.04
   376.9 1577.55     413 1576.46   439.3 1577.54   458.9  1579.4   514.7 1579.12
   554.1 1581.02   570.5 1587.68   577.6 1589.37   596.7 1599.32   606.6 1602.99
   616.4 1608.09   636.3 1616.58     646 1622.94   678.7 1650.63   692.9  1658.5
#Mann= 6 ,-1 , 0
       0      .1       0     240     .04       0   253.3    .045       0
   288.3     .04       0     340    .035       0     540      .1       0
#XS Ineff= 2 , 0
             230  1581.5
Permanent Ineff=
       F       F
Bank Sta=253.3,288.3
XS Rating Curve= 0 ,0
Exp/Cntr=0.3,0.1

Type RM Length L Ch R = 1 ,17777   ,171.9,174.6,169.1
XS GIS Cut Line= 4
  1993435.328515176869.0944681831993449.27529388176642.199021862
1993312.02923579176349.2366196111993304.89883614176217.683674827
#Sta/Elev= 30
       0 1671.26    61.6 1644.44    91.2 1629.76   127.3 1610.97   140.5 1606.05
   167.2 1594.46   189.8 1586.58   196.3 1583.05   209.5 1583.09   222.6 1579.47
     233 1577.92   276.3 1577.19   281.2 1574.91   283.7 1573.11   287.4 1572.42
   305.5 1572.06   322.2 1574.03     338 1575.71   353.2 1575.31   410.6 1578.08
   527.9 1577.81   544.6  1578.7     555 1581.64   561.6 1582.79   564.9 1584.06
   571.1 1587.89   584.2 1594.21     601 1601.62   637.2 1618.85   682.6 1642.49
#Mann= 7 ,-1 , 0
       0     .08       0      30    .035       0     130     .04       0
  227.32    .035       0   281.2    .045       0   322.2    .035       0
  447.32      .1       0
Bank Sta=281.2,322.2
XS Rating Curve= 0 ,0
Exp/Cntr=0.3,0.1

Type RM Length L Ch R = 1 ,17602   ,299.6,294.7,278.2
XS GIS Cut Line= 3
1993639.18843307 176812.443561821993630.25135369 176649.50643818
 1993393.2791079176220.399087042
#Sta/Elev= 30
       0 1630.64    67.2 1614.66    90.2 1610.36     156 1592.68   166.2 1592.53
   199.9 1588.72   214.5 1587.92   229.9 1576.64   233.6 1575.61   254.3 1574.13
   261.1 1572.39   267.4 1572.03   282.4 1572.46   291.7 1574.19   297.4  1576.7
   301.1 1576.93   323.6 1576.36   407.6 1576.97   424.5 1575.29   443.8 1576.58
   458.5 1575.36     468 1576.55   484.9 1575.94   544.7 1579.05   552.2 1581.19
   563.5 1586.58   593.4 1605.84     608 1608.84   623.4 1615.25   653.4 1634.06
#Mann= 6 ,-1 , 0
       0    .035       0      80     .04       0  173.18    .035       0
   254.3    .045       0   291.7    .035       0  443.18      .1       0
Bank Sta=254.3,291.7
XS Rating Curve= 0 ,0
Exp/Cntr=0.3,0.1

Type RM Length L Ch R = 1 ,17307   ,162.6,176.4,191.7
XS GIS Cut Line= 4
1993761.60070018176751.461235357 1993804.7876818176466.660599755
1993570.17732215176272.9027902881993567.84289071176136.338551085
#Sta/Elev= 30
       0 1632.37    52.7 1611.86    62.6 1607.15    72.6 1605.28    82.5 1601.83
   109.1  1598.1   115.7 1595.44   125.7 1588.34   142.3 1588.07   162.2 1583.97
   194.2 1581.71   288.1 1578.94   350.3 1578.59   448.1 1576.25   473.8 1576.56
   494.8 1575.87   507.8 1573.59   524.8 1571.59   546.4 1572.97   566.6 1575.67
   576.3 1581.78   588.6 1583.37   595.7 1586.49   605.7 1593.12   612.1 1599.49
   615.3 1601.66   648.2  1620.7   697.4 1654.95   713.8 1663.23   728.9 1672.63
#Mann= 8 ,-1 , 0
       0    .035       0      10     .06       0     110    .035       0
     210     .04       0  308.06    .035       0  438.06      .1       0
   507.8    .045       0   546.4      .1       0
#XS Ineff= 2 , 0
             350    1581
Permanent Ineff=
       F       F
Bank Sta=507.8,546.4
XS Rating Curve= 0 ,0
Exp/Cntr(USF)=0,0
Exp/Cntr=0.3,0.1

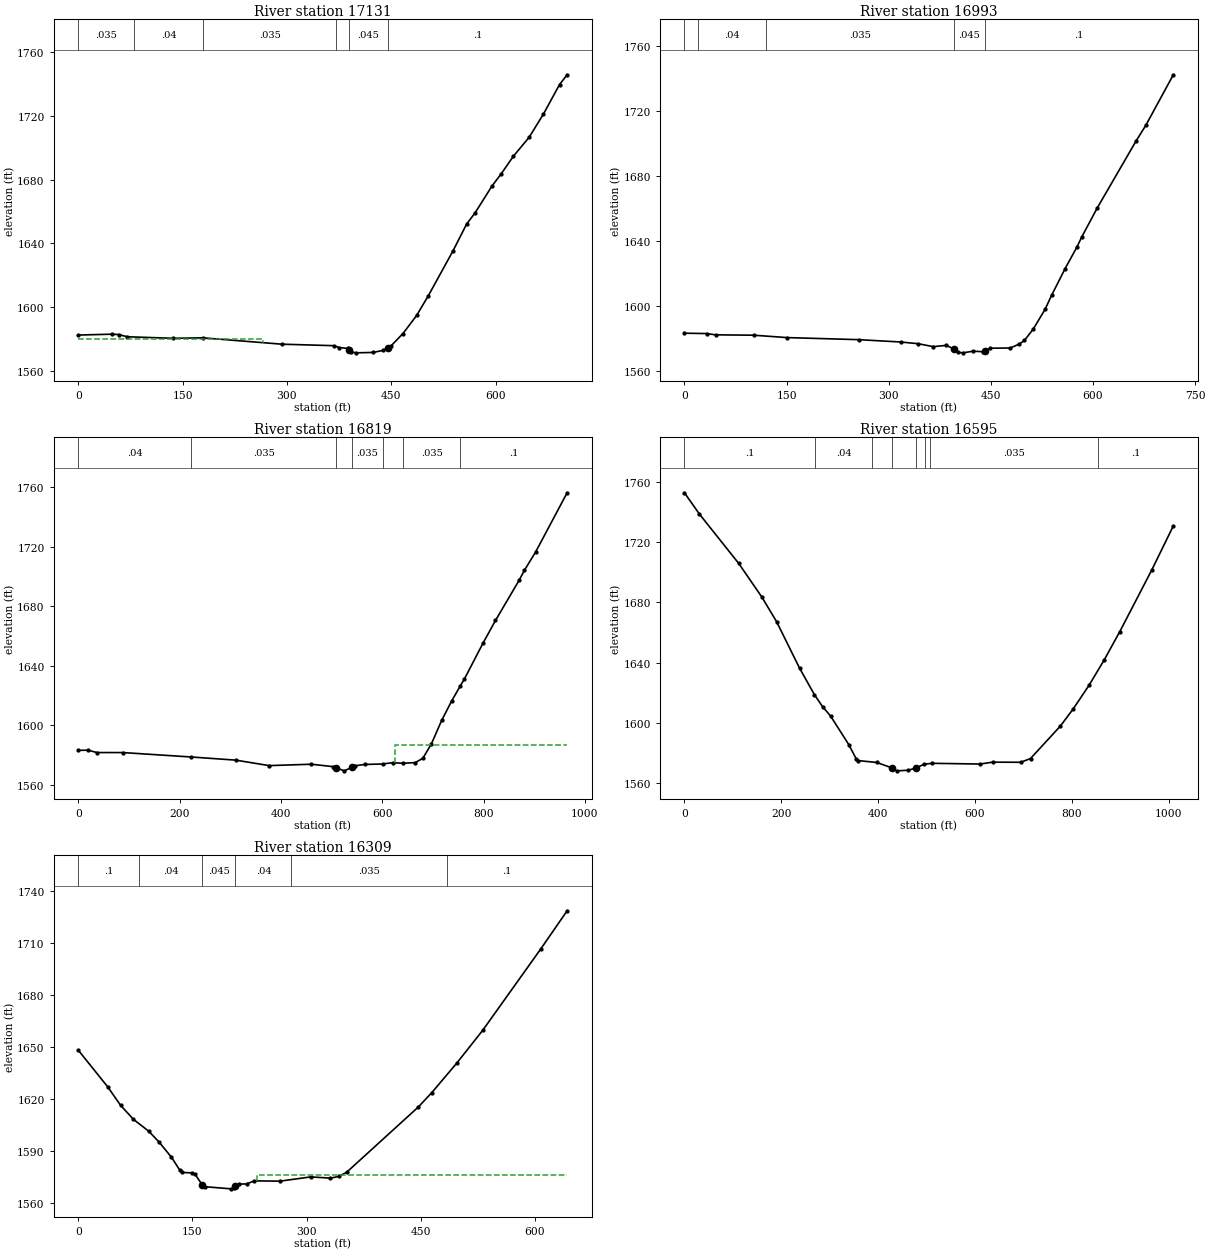
Type RM Length L Ch R = 1 ,17131   ,140,137.9,134.1
XS GIS Cut Line= 3
1993929.45729006176612.3226137491993754.41323321176188.088281014
 1993587.6970117176009.760262611
#Sta/Elev= 30
       0  1582.3      48 1582.84      58 1582.62    70.6 1581.22   136.5 1580.25
   179.1 1580.55   292.7 1576.56   367.2 1575.62   375.3 1574.45   387.2 1573.93
   389.7 1573.17   392.5 1571.75   399.7 1571.12     424 1571.38   438.2 1572.63
     445 1574.12     450 1575.61   466.9 1583.24   486.6 1594.61   503.5 1607.11
   538.9 1635.24   558.5  1652.1   570.8 1659.21   594.8 1675.88   607.9 1683.47
   625.8 1694.75   648.3 1706.56   668.9 1721.17   692.1 1739.75     703 1745.89
#Mann= 6 ,-1 , 0
       0    .035       0      80     .04       0     180    .035       0
     370      .1       0   389.7    .045       0     445      .1       0
#XS Ineff= 2 , 0
             265    1580
Permanent Ineff=
       F       F
Bank Sta=389.7,445
XS Rating Curve= 0 ,0
Exp/Cntr=0.3,0.1

Type RM Length L Ch R = 1 ,16993   ,171.9,173.8,168.4
XS GIS Cut Line= 4
1993950.50547412176557.9789425811993958.89365458176302.787820895
1993826.87906434176032.2322081271993684.48724835175955.753367952
#Sta/Elev= 30
       0 1583.01    32.5 1582.78    45.6    1582   101.4 1581.78   150.7  1580.3
   255.8 1579.03   317.8 1577.58   343.4 1576.52   365.3 1574.72   384.7 1575.51
   395.81573.243   401.8 1571.16   409.1  1570.9   423.9 1571.93   438.3 1571.59
   441.31572.205   449.2 1573.77   478.5 1573.88   491.8 1576.33   499.3 1578.55
   512.3 1585.57   529.6 1597.68   539.2 1606.34   558.8 1622.62   576.4 1636.12
   583.8 1642.57   606.1 1660.11     663 1701.32   677.6 1711.18     718 1742.35
#Mann= 5 ,-1 , 0
       0    .035       0      20     .04       0     120    .035       0
   395.8    .045       0   441.3      .1       0
Bank Sta=395.8,441.3
XS Rating Curve= 0 ,0
Exp/Cntr=0.3,0.1

Type RM Length L Ch R = 1 ,16819   ,239.6,224.7,202
XS GIS Cut Line= 4
1993976.06882343176544.1594081061994084.35425954176190.040080904
1993952.50720479175909.354525855     1993693.938      175790.807
#Sta/Elev= 30
       0 1583.26    19.5 1583.36    36.7 1581.77    88.1 1581.76   222.9 1578.79
   311.1 1576.67   376.7    1573     460 1573.93   502.5 1572.33   508.81571.472
   525.3 1569.49   539.91571.879     547 1572.91   565.2 1573.78   600.6 1574.08
   620.9 1574.98   640.6 1574.56   665.3 1575.03   680.1 1577.93   696.8 1587.45
   717.2  1603.3   736.9 1616.36   754.3  1626.7   762.2 1631.21   798.8 1655.19
   823.5 1670.47   870.5 1697.65   880.5  1704.1   902.8 1716.51   964.9 1756.21
#Mann= 7 ,-1 , 0
       0     .04       0   222.9    .035       0   508.8    .045       0
   539.9    .035       0   600.6      .1       0   640.6    .035       0
   754.3      .1       0
#XS Ineff= 2 , 0
                          625.55         1587.04
Permanent Ineff=
       F       F
Bank Sta=508.8,539.9
XS Rating Curve= 0 ,0
Exp/Cntr=0.3,0.1

Type RM Length L Ch R = 1 ,16595   ,306.9,285.2,250.9
XS GIS Cut Line= 4
 1994642.7034867175991.1856470121994355.41260728176067.514897172
1993971.43520386175800.288504927     1993729.327      175764.366
#Sta/Elev= 30
       0 1753.02    30.6 1738.95   112.1 1705.98   159.6 1683.73   190.2 1667.29
   237.7 1636.32   268.3 1618.74   285.2  1610.7   301.7 1604.48   339.4  1585.4
   355.1  1575.7   359.1 1574.78   397.2 1573.52   429.11569.853   438.4 1567.96
   461.9 1568.35   477.61569.799   494.9 1572.34   511.4 1572.97   610.9 1572.49
   636.3 1573.74   694.8 1573.66   714.8 1576.15   776.4 1597.72     803 1609.17
   835.5 1624.78   867.3 1641.93   899.2 1660.59   965.5 1701.77  1009.8 1730.96
#Mann= 8 ,-1 , 0
       0      .1       0     270     .04       0  387.26    .035       0
   429.1    .045       0   477.6    .035       0  497.26     .04       0
  507.26    .035       0  855.07      .1       0
Bank Sta=429.1,477.6
XS Rating Curve= 0 ,0
Exp/Cntr=0.3,0.1

Type RM Length L Ch R = 1 ,16309   ,113.9,111.1,105.7
XS GIS Cut Line= 3
1994355.41260728175690.1540550011994001.22024487175776.534246647
     1993729.685      175717.971
#Sta/Elev= 30
       0  1648.2    38.7 1627.03    55.6 1616.38    72.5 1608.28    92.5 1601.47
   106.1  1595.2   122.4 1586.45   133.3    1579   136.6 1577.64   149.5  1577.4
   153.5 1576.55  163.091570.376     167 1569.38   200.8 1568.18   204.2 1568.58
   206.5 1569.72   210.9 1570.93   221.1    1571   231.2 1572.79     265 1572.61
   305.5 1575.07   331.4 1574.36   342.3 1575.34   352.8 1577.81   446.8 1615.39
   464.6 1623.74   497.2 1640.66   531.4 1659.65   607.6 1706.56   642.4 1728.69
#Mann= 6 ,-1 , 0
       0      .1       0      80     .04       0  163.09    .045       0
   206.5     .04       0     280    .035       0  484.57      .1       0
#XS Ineff= 2 , 0
                             235            1576
Permanent Ineff=
       F       F
Bank Sta=163.09,206.5
XS Rating Curve= 0 ,0
Exp/Cntr=0.3,0.1