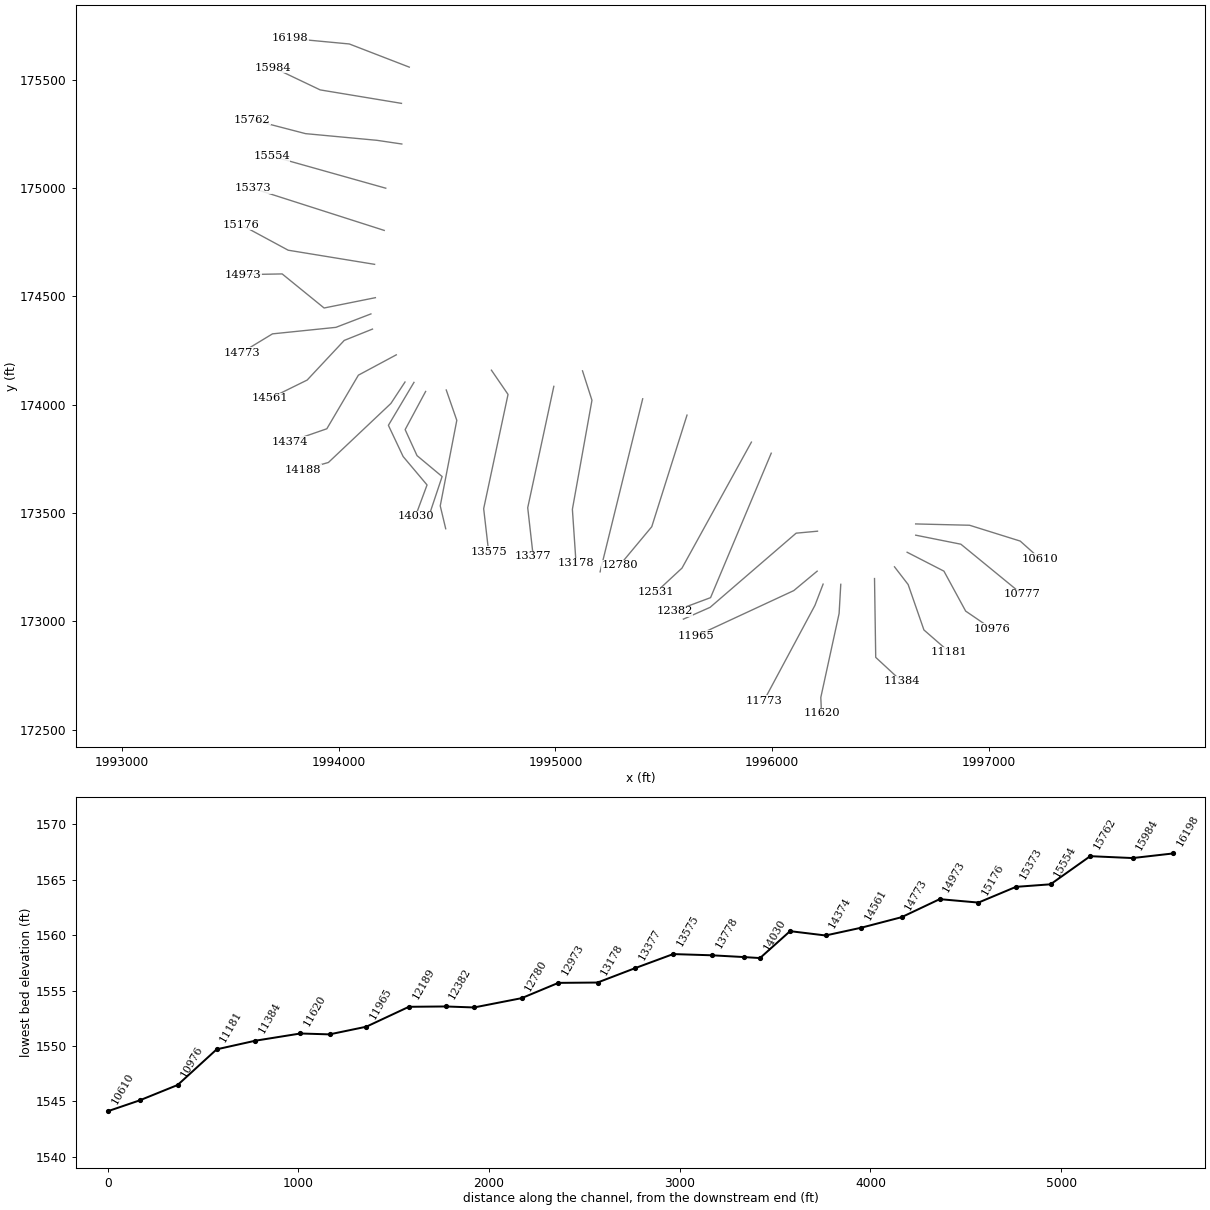
HEC-RAS study LICKCK.prj: LICKCK

--- LICKCK.g01 (geometry) --- (continued)

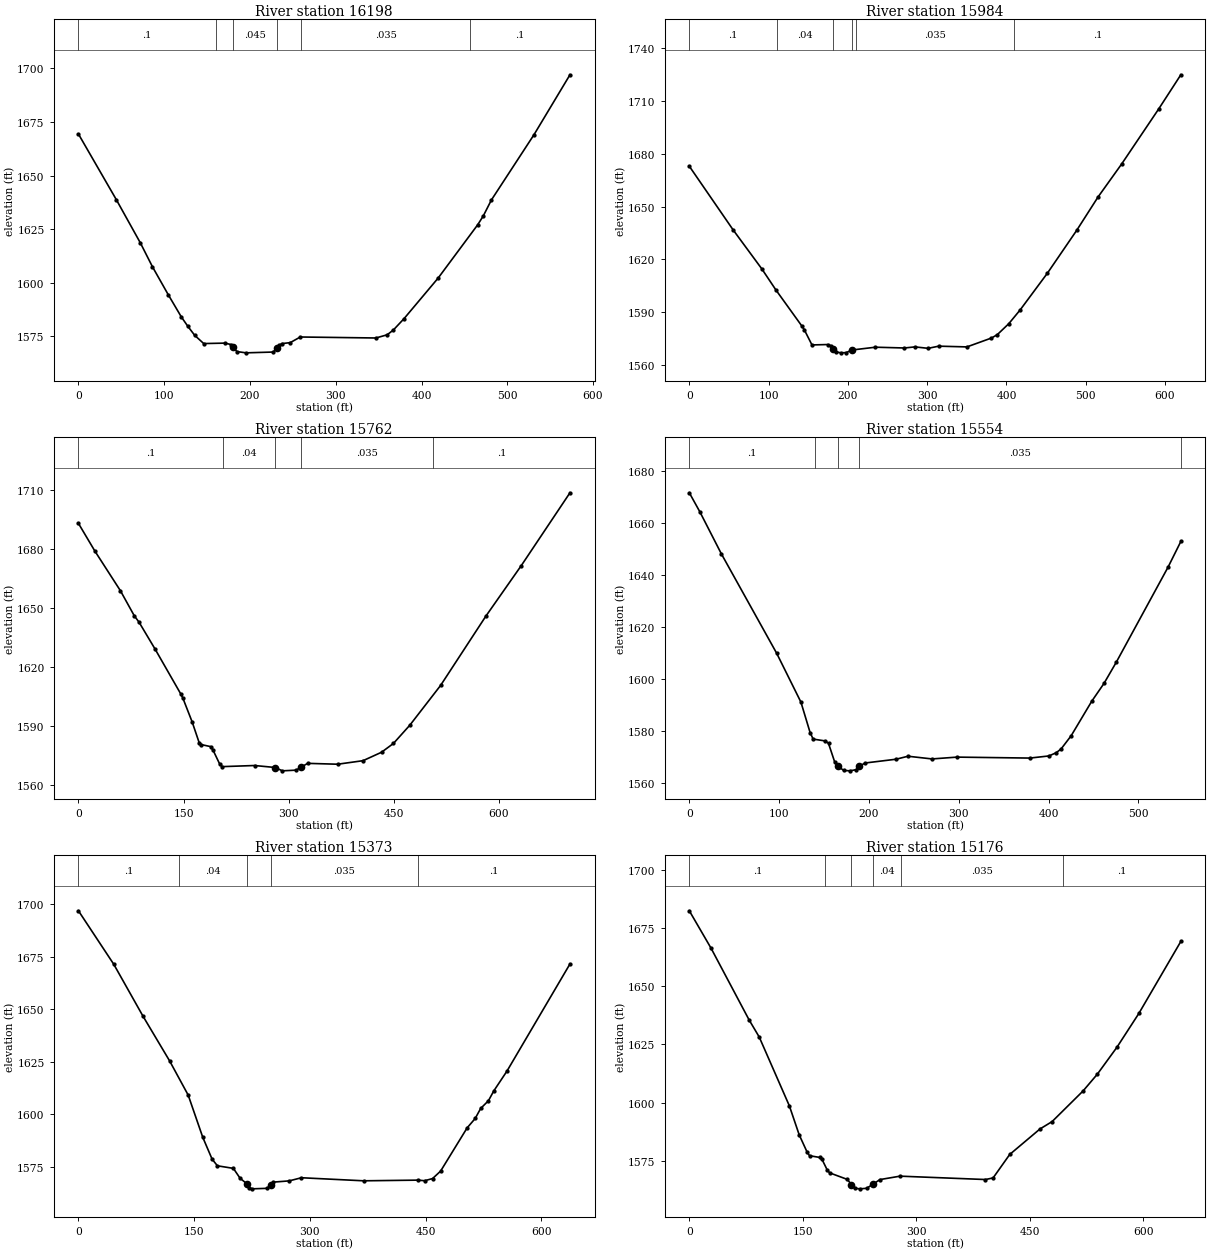
Type RM Length L Ch R = 1 ,16198   ,207.5,214.1,223.3
XS GIS Cut Line= 3
1994326.14858267175558.3555903391994049.61393892175665.280695681
1993774.22968398175691.293859545
#Sta/Elev= 30
       0 1669.34    44.1 1638.81    72.3 1618.54    86.3 1607.49   104.8 1594.41
     120  1584.1   127.7 1579.67   135.6 1575.52   146.1  1571.7   170.8 1571.91
   177.8 1571.26     180  1570.1   184.8 1567.97   195.4 1567.38     227 1567.75
   231.7 1569.64   234.2 1570.95   237.6 1571.71   246.9 1572.13   258.7 1574.76
   346.8  1574.3   359.9 1575.78   367.1 1577.98   379.7 1583.34   419.3 1602.17
   465.4 1626.98     472 1631.15   481.5 1638.61   531.3 1669.11   573.1 1696.94
#Mann= 6 ,-1 , 0
       0      .1       0     160     .04       0     180    .045       0
   231.7     .04       0     260    .035       0  456.49      .1       0
Bank Sta=180,231.7
XS Rating Curve= 0 ,0
Exp/Cntr=0.3,0.1

Type RM Length L Ch R = 1 ,15984   ,216.8,222.4,226.6
XS GIS Cut Line= 3
1994290.13317046175391.1333185791993915.19051245175453.293283465
     1993698.719      175556.473
#Sta/Elev= 30
       0    1673    55.2 1636.86    91.7 1614.51   109.3 1602.64   141.6 1582.41
   144.9 1580.19   154.7 1571.45   174.8 1571.68   178.1 1571.05   181.5 1569.18
   184.8 1567.47   191.4 1566.96   198.1 1567.11   204.7 1568.55   234.7 1570.16
   271.3 1569.72   284.6 1570.34   301.2 1569.52   314.5 1570.75   350.1 1570.33
   381.1 1575.38   388.4 1577.29   402.9 1583.51   417.2 1591.31   451.7 1612.27
   488.6 1636.58   515.6 1655.59   545.2 1674.22   591.9 1705.48   619.9 1724.95
#Mann= 6 ,-1 , 0
       0      .1       0     110     .04       0   181.5    .045       0
   204.7     .04       0     210    .035       0  410.06      .1       0
Bank Sta=181.5,204.7
XS Rating Curve= 0 ,0
Exp/Cntr=0.3,0.1

Type RM Length L Ch R = 1 ,15762   ,208.7,208,206.1
XS GIS Cut Line= 4
1994291.73540711175203.5089531821994176.71188059175220.583170975
1993847.75332517      175251.357     1993601.017      175315.501
#Sta/Elev= 30
       0 1693.14    23.4 1679.08    59.9 1658.86    79.8 1646.03    86.4 1642.89
   109.6 1629.01   145.9  1606.4   149.2 1604.04   162.4 1591.96   172.3  1581.5
   175.6 1580.48   188.8 1579.46   192.1  1577.7   201.9 1570.38   205.2 1569.27
   251.4 1569.84   281.2 1568.83   290.9 1567.13   310.7 1567.48   317.2 1568.85
   327.2 1570.94     370  1570.5   406.2  1572.3   432.6 1576.59   449.6 1581.07
   472.9 1590.32   516.9  1610.6   581.4 1645.82   632.2 1671.69   701.6 1708.72
#Mann= 5 ,-1 , 0
       0      .1       0  206.28     .04       0   281.2    .045       0
   317.2    .035       0  506.68      .1       0
Bank Sta=281.2,317.2
XS Rating Curve= 0 ,0
Exp/Cntr=0.3,0.1

Type RM Length L Ch R = 1 ,15554   ,182.2,181.4,180.8
XS GIS Cut Line= 2
1994217.65078165174999.5384005111993690.83408449175147.815990851
#Sta/Elev= 30
       0 1671.78    11.8 1664.41    35.7 1648.24    97.3  1609.9   124.3 1591.07
   134.5 1579.35   137.9 1576.82   151.6 1576.11     155 1575.17   161.8 1568.09
   165.2  1566.4     172 1564.75   178.8 1564.59   185.7 1565.03   189.1  1566.3
   195.7 1567.61   230.3 1569.07   243.5 1570.22   270.2 1569.18   298.1 1569.88
   379.2 1569.51   400.4 1570.33   408.5 1571.57     414 1573.04   425.2 1578.13
   448.1 1591.42   461.7 1598.27   475.4 1606.45     533 1643.07   547.3 1653.01
#Mann= 5 ,-1 , 0
       0      .1       0     140    .035       0   165.2    .045       0
   189.1    .035       0  547.29      .1       0
Bank Sta=165.2,189.1
XS Rating Curve= 0 ,0
Exp/Cntr=0.3,0.1

Type RM Length L Ch R = 1 ,15373   ,193.4,196.8,200.7
XS GIS Cut Line= 2
1994210.54246563174804.706695681      1993603.64      174999.131
#Sta/Elev= 30
       0 1696.91    45.8 1671.42    83.7 1646.67   118.2 1625.36   142.3 1609.05
   161.2 1588.93   173.3 1578.52   180.2 1575.34   200.9 1574.12   209.6  1569.4
   218.1 1566.86   221.5 1564.95     225 1564.36   244.7  1564.6   249.1 1566.34
   252.5 1567.56   273.2 1568.15   289.1 1569.65   369.7 1568.19     440 1568.51
   448.9 1568.23   459.2 1569.27   469.6 1572.83     504 1593.44   514.4  1597.9
   521.5 1602.67   531.6 1606.37   538.5 1611.02   555.7 1620.54   637.3 1671.56
#Mann= 5 ,-1 , 0
       0      .1       0     130     .04       0   218.1    .045       0
   249.1    .035       0     440      .1       0
Bank Sta=218.1,249.1
XS Rating Curve= 0 ,0
Exp/Cntr=0.3,0.1

Type RM Length L Ch R = 1 ,15176   ,215.5,203.2,189.4
XS GIS Cut Line= 3
1994166.20693912174648.0638604751993767.48846563174713.331341988
      1993551.24      174830.171
#Sta/Elev= 30
       0 1682.44    28.7 1666.39    79.1 1635.51    92.4 1628.21   132.3 1598.59
   145.3 1586.13   155.6 1578.83   158.9 1577.18   172.2 1576.45   175.5 1575.56
   182.2 1571.13   185.5 1569.81   208.8    1567   214.4 1564.78   218.7 1563.17
   225.4 1562.94   234.4 1563.17   242.9 1564.95     252 1566.92   278.6 1568.39
   391.5 1566.94   401.6 1567.63   423.6 1577.72   463.6 1588.67   479.6 1591.84
   520.6 1605.02   539.3 1612.17   565.4 1623.82   594.3 1638.32   649.8 1669.26
#Mann= 6 ,-1 , 0
       0      .1       0     180     .04       0   214.4    .045       0
   242.9     .04       0     280    .035       0  494.03      .1       0
Bank Sta=214.4,242.9
XS Rating Curve= 0 ,0
Exp/Cntr=0.3,0.1

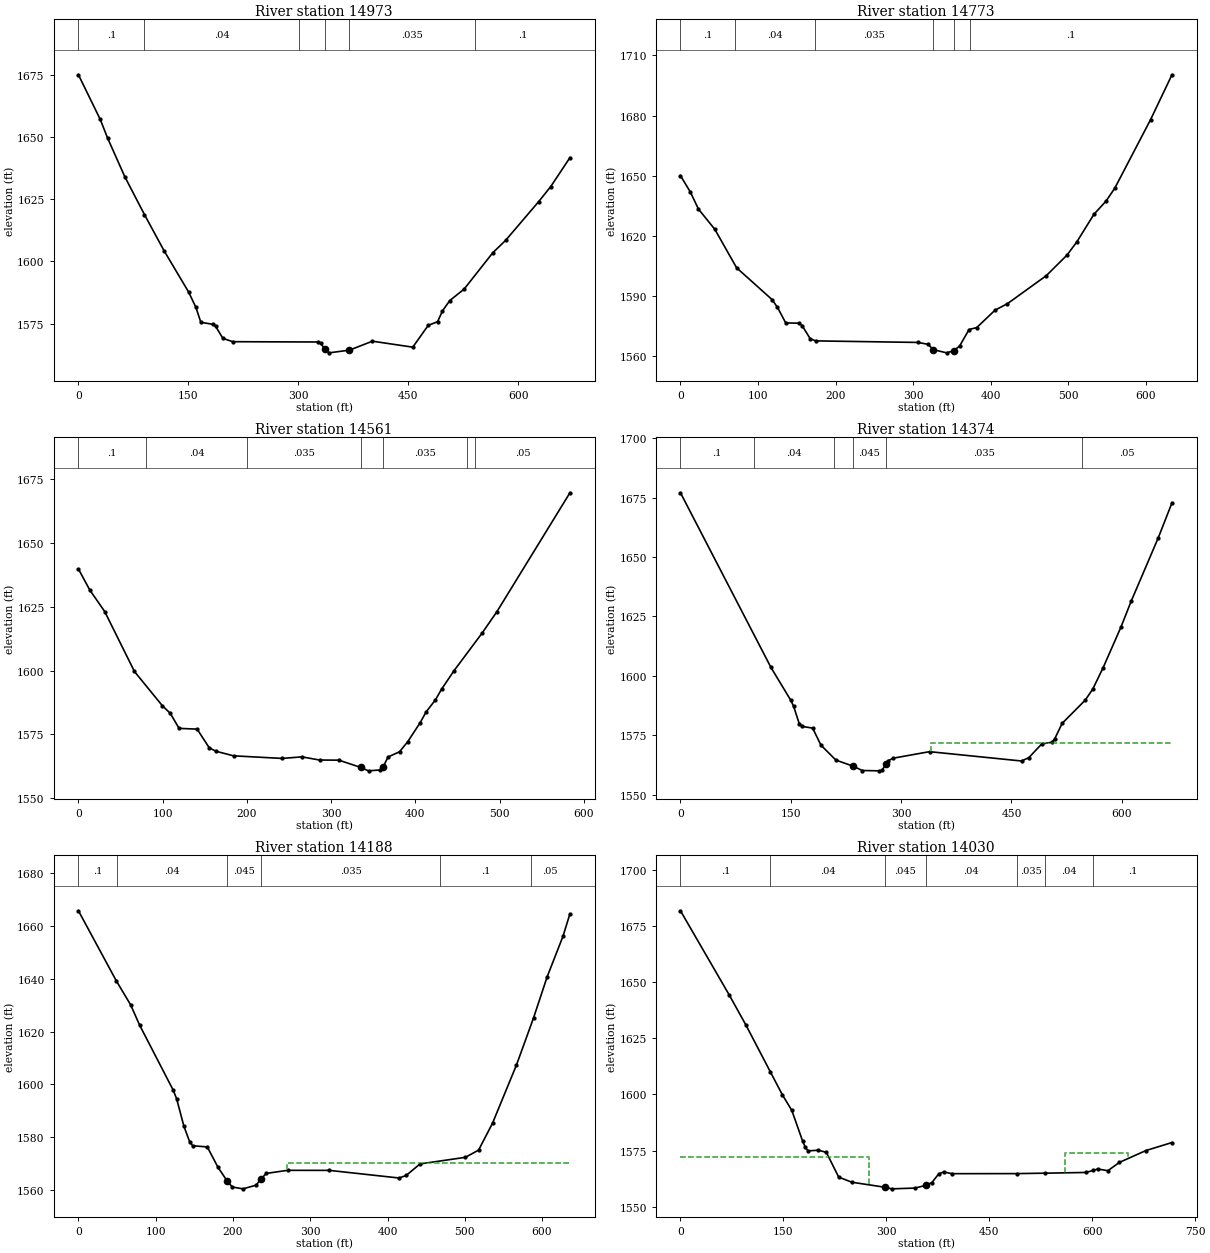
Type RM Length L Ch R = 1 ,14973   ,177,200,218.6
XS GIS Cut Line= 4
1994169.83230799174494.1910211841993933.25340956174446.542646934
1993739.81727269174603.8379127561993560.00314123174600.481145579
#Sta/Elev= 30
       0 1675.02    29.8 1657.05    39.8 1649.56    63.2 1634.09      90 1618.85
   116.8 1604.31   150.3  1587.7   160.3 1581.48     167 1575.52   183.7  1574.7
   187.1 1573.93   197.1 1569.06   210.5 1567.73   326.3 1567.61     331 1567.02
   335.7 1564.75   341.9 1563.25   369.6 1564.33   401.1 1567.93   456.1 1565.53
   477.2  1574.3   489.9 1575.76   496.6 1580.09   506.5 1584.24   526.2 1588.89
   565.1 1603.43   582.8 1608.48   627.9 1624.05   644.3 1630.08   670.5 1641.72
#Mann= 6 ,-1 , 0
       0      .1       0      90     .04       0  301.33    .035       0
   335.7    .045       0   369.6    .035       0  540.65      .1       0
Bank Sta=335.7,369.6
XS Rating Curve= 0 ,0
Exp/Cntr=0.3,0.1

Type RM Length L Ch R = 1 ,14773   ,195.4,211.6,228.5
XS GIS Cut Line= 4
1994149.17421619 174419.21889408 1993987.7998403174357.230070613
1993695.14605379174327.164556981 1993552.7256214174240.690724608
#Sta/Elev= 30
       0 1650.03    12.7  1641.9    23.2 1633.34    44.3 1623.25    72.4 1604.05
   118.1 1588.19   125.1 1584.29   135.7 1576.55   153.2 1576.41   156.8 1575.23
   167.3 1568.66   174.4 1567.58   306.3 1566.81   319.4 1565.86   325.9 1563.22
   343.1 1561.62   352.3 1562.66   359.9    1565   372.1 1573.26     382 1574.22
   405.5 1582.89   421.6 1586.16   471.7 1600.14   498.4 1610.41     511 1616.97
   533.1 1630.74   548.7 1637.34     560  1643.8   606.1 1677.98   633.7 1700.36
#Mann= 6 ,-1 , 0
       0      .1       0      70     .04       0  172.87    .035       0
   325.9    .045       0   352.3    .035       0  372.87      .1       0
Bank Sta=325.9,352.3
XS Rating Curve= 0 ,0
Exp/Cntr=0.3,0.1

Type RM Length L Ch R = 1 ,14561   ,186.4,186.8,192.1
XS GIS Cut Line= 4
1994156.43146888174349.2088022831994026.19684214174296.927591304
 1993855.0978376174113.8955119051993682.35344486174028.819706133
#Sta/Elev= 30
       0 1639.84    13.5 1631.59    31.2 1623.16    66.5 1599.64    99.6 1586.22
   108.9 1583.27   119.5 1577.33   140.9 1577.03   155.3 1569.69   163.2 1568.36
   184.1 1566.56   241.8 1565.54   265.3 1566.15   286.2 1564.91   309.1 1564.86
     335 1562.02   344.3 1560.67   358.2 1561.02   361.9 1562.35   367.5 1566.11
   381.1 1568.15   390.7 1572.03   405.4 1579.44   412.7 1583.78   423.7  1588.5
     431 1592.67   445.6 1599.86   478.9  1614.6   496.8 1623.15   583.4 1669.75
#Mann= 7 ,-1 , 0
       0      .1       0      80     .04       0  200.34    .035       0
     335    .045       0   361.9    .035       0  460.89      .1       0
  470.89     .05       0
Bank Sta=335,361.9
XS Rating Curve= 0 ,0
Exp/Cntr=0.3,0.1

Type RM Length L Ch R = 1 ,14374   ,195.2,186.3,176.9
XS GIS Cut Line= 4
1994266.19752689174230.3473786031994091.39116241174136.487261269
1993945.88128246173889.0984103381993773.29188702173829.062458986
#Sta/Elev= 30
       0    1677   122.9 1603.55     150 1589.65   153.7 1587.23   161.6 1579.71
   164.9 1578.68   179.7 1577.96   190.9 1570.81   211.3 1564.49   233.9 1562.03
   247.2 1560.11   269.5 1559.97   273.9 1560.18   279.5 1562.79   282.5 1564.24
   289.1 1565.29   338.6 1568.04   463.7 1564.11   473.6 1565.52   491.1 1571.28
     505 1572.01   508.8 1573.46   518.9 1579.95   550.2 1589.69   560.6 1594.43
   574.5 1603.32   598.8 1620.44   612.7 1631.34   649.5 1658.01   668.2 1672.76
#Mann= 6 ,-1 , 0
       0      .1       0     100     .04       0  208.41    .035       0
   233.9    .045       0   279.5    .035       0  545.42     .05       0
#XS Ineff= 2 , 0
                          340.34         1571.66
Permanent Ineff=
       F       F
Bank Sta=233.9,279.5
XS Rating Curve= 0 ,0
Exp/Cntr=0.3,0.1

Type RM Length L Ch R = 1 ,14188   ,66.3,157.7,201.1
XS GIS Cut Line= 4
1994306.43220207174104.8924280331994241.28773003174005.819982305
1993953.08631777173733.4696477141993836.71284465 173700.26721184
#Sta/Elev= 30
       0 1665.82    49.1  1639.2    67.5 1630.18    79.3 1622.38   122.5 1597.88
   127.1  1594.5   136.4 1584.21   144.2    1578     148  1576.7   166.8 1576.25
   180.7 1568.47   192.1 1563.51   199.1 1561.05     213 1560.36     230 1561.76
   236.2 1564.12   243.2 1566.21   270.6 1567.38   324.8 1567.36   414.9 1564.47
   424.1 1565.42   442.1 1569.81   500.8 1572.31   517.9 1575.06   535.9 1585.25
   566.9 1607.33     589 1625.19   606.6 1640.77   627.1 1656.15   636.1 1664.67
#Mann= 6 ,-1 , 0
       0      .1       0      50     .04       0   192.1    .045       0
   236.2    .035       0  468.57      .1       0   585.1     .05       0
#XS Ineff= 2 , 0
                          270.14          1570.1
Permanent Ineff=
       F       F
Bank Sta=192.1,236.2
XS Rating Curve= 0 ,0
Exp/Cntr=0.5,0.3

Type RM Length L Ch R = 1 ,14030   ,138.6,84.1,70.6
XS GIS Cut Line= 5
1994347.77197819174103.1869810151994229.84412288173904.994530821
1994297.78654837173760.8940157271994408.10482731173629.760689018
1994354.27039217173484.413577019
#Sta/Elev= 30
       0 1681.91    71.3 1644.24    95.3 1631.02   131.2 1609.97   148.4 1599.92
   162.3 1592.88   178.2 1579.06     182 1576.48   185.8 1574.85   201.1 1575.16
   212.6 1574.19   230.6 1563.16   249.7 1560.88   298.4 1558.62   307.8 1557.93
   341.8 1558.27   357.3 1559.46   366.4 1560.72   376.3 1564.58   383.7 1565.46
   395.7 1564.69     490 1564.72   530.7 1564.91   590.6 1565.23   601.9 1566.15
   608.1 1566.78   622.9 1566.01   639.6 1569.71   678.5 1575.02   716.3 1578.58
#Mann= 7 ,-1 , 0
       0      .1       0   131.2     .04       0   298.4    .045       0
   357.3     .04       0     490    .035       0   530.7     .04       0
   601.9      .1       0
#XS Ineff= 3 ,-1
       0   274.4  1572.2   381.3   559.9  1564.6     560  652.32 1573.77
Permanent Ineff=
       F       F       F
Bank Sta=298.4,357.3
XS Rating Curve= 0 ,0
Exp/Cntr(USF)=0,0
Exp/Cntr=0.5,0.3

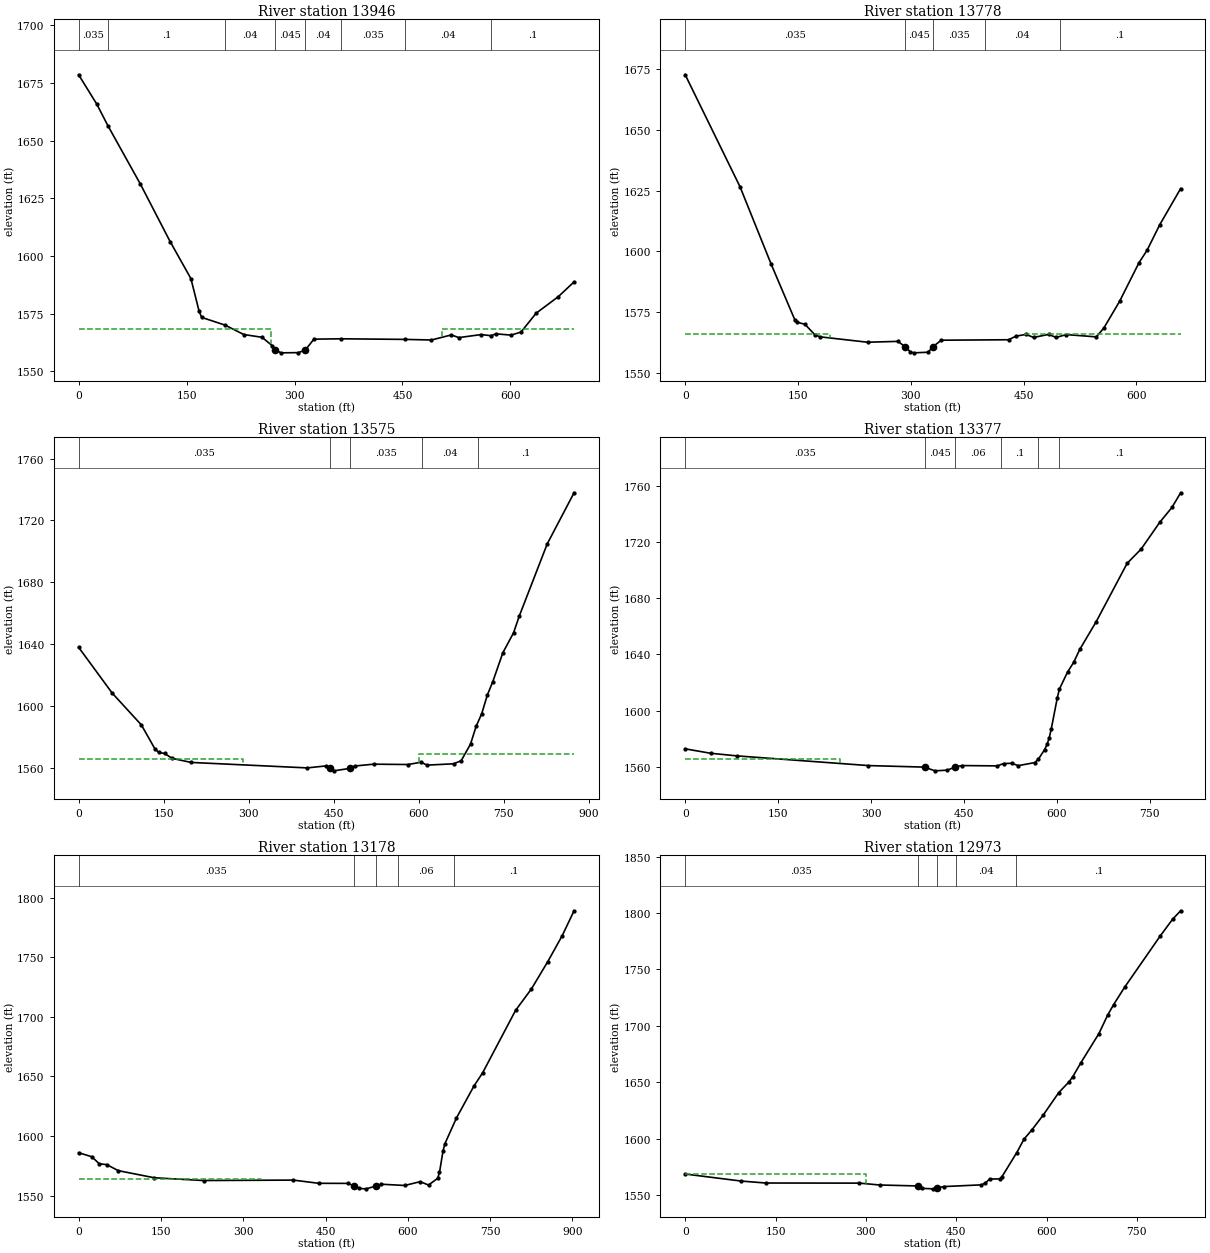
Type RM Length L Ch R = 1 ,13946   ,190.2,168.1,152.3
XS GIS Cut Line= 5
1994401.52813873174061.3033172111994307.05446207173885.113223584
1994361.86669138173765.0959923181994477.63170026173668.548797747
1994412.44675194173473.333758552
#Sta/Elev= 30
       0 1678.57    25.3 1665.81    40.6 1656.53    85.9 1631.13   127.1 1606.28
     156 1590.22   167.2 1576.31   170.9 1573.39   203.6 1570.03   229.5 1565.96
   254.8 1564.76   269.2 1561.08   272.8  1559.4   281.1 1558.02   305.3 1558.11
  315.031559.249   326.9 1563.95   364.2 1564.11   452.9 1563.85   490.2 1563.59
   517.9 1565.78   528.3 1564.63   559.4 1565.94   572.9 1565.46   580.2 1566.26
   600.9 1565.69   614.7 1567.04   635.7  1575.2   666.5 1582.37   688.4 1588.78
#Mann= 8 ,-1 , 0
       0    .035       0    40.6      .1       0   203.6     .04       0
   272.8    .045       0  315.03     .04       0   364.2    .035       0
   452.9     .04       0   572.9      .1       0
#XS Ineff= 2 , 0
           266.8  1568.5     505          1568.5
Permanent Ineff=
       F       F
Bank Sta=272.8,315.03
XS Rating Curve= 0 ,0
Exp/Cntr(USF)=0,0
Exp/Cntr=0.5,0.3

Type RM Length L Ch R = 1 ,13778   ,203.7,203.1,202.7
XS GIS Cut Line= 4
1994496.69651277174068.0735127681994545.34021997173928.005600994
1994468.96684572 173533.169666191994494.15328245173427.611310698
#Sta/Elev= 30
       0 1672.64    72.9 1626.55   114.5 1594.55   145.8 1571.77   149.2 1570.78
   159.3 1569.91   172.6 1565.58   179.3 1564.77   242.5 1562.55   282.9  1562.9
   292.6 1560.68   299.6 1558.54   304.1 1558.18     323 1558.43   329.7 1560.74
   340.5 1563.38   430.1 1563.57     440 1565.05   453.3 1565.77   463.3 1564.53
   483.4 1565.75   493.4 1564.52   506.8 1565.69   546.9 1564.75     557 1568.48
   577.7 1579.33   603.6 1595.28   614.3 1600.38   631.2 1610.91     659  1625.8
#Mann= 5 ,-1 , 0
       0    .035       0   292.6    .045       0   329.7    .035       0
  398.27     .04       0  498.27      .1       0
#XS Ineff= 2 , 0
             192    1566  452.34            1566
Permanent Ineff=
       F       F
Bank Sta=292.6,329.7
XS Rating Curve= 0 ,0
Exp/Cntr=0.3,0.1

Type RM Length L Ch R = 1 ,13575   ,198.2,198.1,198.5
XS GIS Cut Line= 4
1994705.00454808174159.5651624111994781.66537803174047.609187084
1994669.26682725173520.2006026381994692.15731776173322.359985877
#Sta/Elev= 30
       0 1638.08    59.1 1608.56   110.8  1587.9   134.7 1572.41   141.5 1570.15
   151.6 1569.52     165 1566.34   198.6 1563.72   403.2 1560.19   436.7 1561.48
     443 1560.19   450.1 1558.29   478.2 1559.86     487  1561.4   520.4 1562.59
     581 1562.37   604.4 1563.86   614.5 1561.98   661.5 1562.84   674.9 1564.81
   691.4 1575.56   701.3    1587   711.2 1595.23   721.1 1607.27   730.8 1615.96
   748.5 1634.59   767.4 1647.47   777.3 1658.12   826.8  1704.9   874.1 1737.88
#Mann= 5 ,-1 , 0
       0    .035       0     443    .045       0   478.2    .035       0
  605.69     .04       0  704.94      .1       0
#XS Ineff= 2 , 0
             290    1566     600          1569.1
Permanent Ineff=
       F       F
Bank Sta=443,478.2
XS Rating Curve= 0 ,0
Exp/Cntr=0.3,0.1

Type RM Length L Ch R = 1 ,13377   ,197.4,198.6,199.8
XS GIS Cut Line= 3
     1994992.877      174084.9281994872.44882289173524.523623822
1994897.89236719173299.599077675
#Sta/Elev= 30
       0 1572.69    41.1 1569.54    84.3 1567.65   295.7 1560.78   386.2 1559.68
   403.1 1557.03   423.2 1557.52   436.1 1559.85   446.7 1560.79   503.7 1560.56
   513.8  1562.2   527.2 1562.41   537.3 1560.72   564.2 1562.91     570 1565.35
   579.9 1572.03   584.1 1575.83   587.4 1580.48   590.7 1586.65   600.6 1609.22
   603.9 1615.22   617.1  1627.4     627 1634.32   636.9  1643.6   663.3 1663.25
   713.3 1704.84     736 1715.05   765.7 1733.92   785.5 1744.58   799.6 1755.05
#Mann= 6 ,-1 , 0
       0    .035       0   386.2    .045       0   436.1     .06       0
     510      .1       0     570     .04       0   603.2      .1       0
#XS Ineff= 2 , 0
             250  1565.5
Permanent Ineff=
       F       F
Bank Sta=386.2,436.1
XS Rating Curve= 0 ,0
Exp/Cntr=0.3,0.1

Type RM Length L Ch R = 1 ,13178   ,207.4,205.7,205.4
XS GIS Cut Line= 4
1995125.14388702174156.4955084161995168.72931776174020.571843006
1995078.51283266173517.318588515 1995095.3393107173268.929134165
#Sta/Elev= 30
       0 1586.01    23.9 1582.67    37.7 1576.73    51.4 1576.03    72.1    1571
   137.9    1565   227.7 1562.69   391.2 1563.06   437.7 1560.36   491.1 1560.29
   501.1 1558.31   511.1 1556.01   523.9 1555.72   541.3 1557.94     551 1559.61
   594.4 1558.54   622.5 1561.74   637.7 1558.91   654.4 1564.53   657.7 1569.45
   664.2 1587.51   667.5 1593.48   688.6  1615.1   720.1 1641.59   736.6 1653.24
   796.4  1705.4   825.4 1723.49     855 1746.24   881.3 1767.98     903 1788.95
#Mann= 5 ,-1 , 0
       0    .035       0   501.1    .045       0   541.3    .035       0
  582.74     .06       0  684.02      .1       0
#XS Ineff= 2 , 0
             332    1564
Permanent Ineff=
       F       F
Bank Sta=501.1,541.3
XS Rating Curve= 0 ,0
Exp/Cntr=0.3,0.1

Type RM Length L Ch R = 1 ,12973   ,194.2,192.4,191.8
XS GIS Cut Line= 2
     1995402.791      174027.428     1995206.324      173228.503
#Sta/Elev= 30
       0 1568.81    93.2 1562.56   133.7 1560.85   289.2 1560.75     323 1559.09
   385.9 1558.25   393.9  1556.1   410.8 1555.69   418.71556.569   429.2 1557.69
   491.9 1559.23   498.6 1560.85   505.4 1564.35   522.3  1564.5   525.7 1566.21
   550.6 1587.81   562.8 1599.87   575.7 1607.89   594.7 1621.21   620.3 1640.93
   637.2 1650.38   643.5 1654.95     657 1667.36   686.9 1693.15   701.4 1709.46
   711.5 1718.97   729.8 1734.37   789.2 1779.98   809.5 1794.62   822.7 1801.99
#Mann= 5 ,-1 , 0
       0    .035       0   385.9    .045       0   418.7    .035       0
     450     .04       0     550      .1       0
#XS Ineff= 2 , 0
          300.28 1568.84
Permanent Ineff=
       F       F
Bank Sta=385.9,418.7
XS Rating Curve= 0 ,0
Exp/Cntr=0.3,0.1

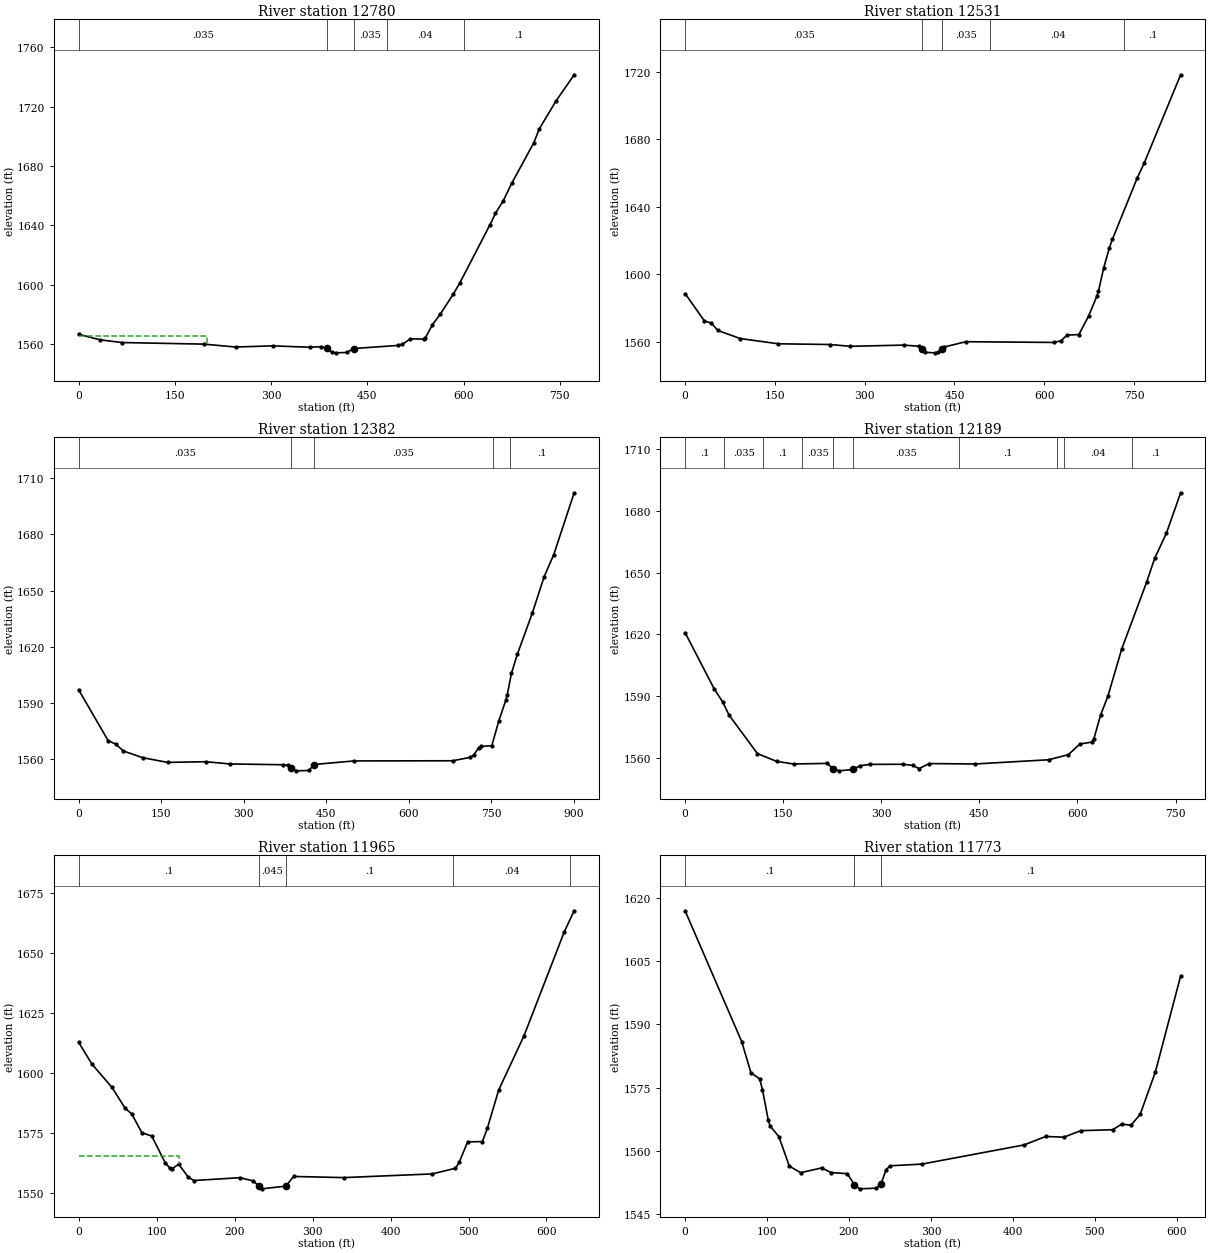
Type RM Length L Ch R = 1 ,12780   ,253.3,249.6,242.9
XS GIS Cut Line= 3
     1995607.206      173952.1021995444.62678816173436.915399787
1995296.21173167173258.652416618
#Sta/Elev= 30
       0 1566.82    33.1 1563.09    67.5 1561.24   195.2 1560.17   244.9 1558.22
   302.4 1559.03   359.9 1558.06   377.2 1558.44   387.5 1557.36   394.4 1554.67
   401.2 1554.31   417.5 1554.55   428.8 1557.21   497.6 1559.28   504.5 1559.98
   516.8 1563.73   537.8 1563.56   540.4 1564.46   551.3  1573.2   563.7 1580.43
   583.6 1593.66   593.8 1601.15     641  1640.5   649.5 1648.12   661.5 1656.51
   675.1 1668.54   709.3 1695.63   717.8 1704.95   743.4 1723.44   772.2 1741.39
#Mann= 5 ,-1 , 0
       0    .035       0   387.5    .045       0   428.8    .035       0
     480     .04       0  600.23      .1       0
#XS Ineff= 2 , 0
             200 1565.83
Permanent Ineff=
       F       F
Bank Sta=387.5,428.8
XS Rating Curve= 0 ,0
Exp/Cntr=0.3,0.1

Type RM Length L Ch R = 1 ,12531   ,145.8,148.4,151.4
XS GIS Cut Line= 3
1995904.23112875173827.4239297721995584.08727811173245.955343762
     1995463.854      173134.315
#Sta/Elev= 30
       0 1588.62    32.3 1572.34    43.6 1571.16    54.8 1566.72    92.1 1561.94
   155.9 1558.83     242 1558.41   275.7 1557.34   365.6 1558.06   391.4 1557.34
   395.6  1555.7   401.4 1553.76   417.4 1553.47   423.1 1553.83   429.3  1555.8
   433.1 1556.96     469 1560.07   616.3 1559.63   627.8 1560.61   638.1 1563.97
   657.8 1564.31   673.9 1575.17   687.8 1586.99   690.5  1589.9   699.4 1604.01
   708.7 1615.66   713.9 1620.82   755.1 1656.98   766.8 1665.81   827.8  1718.3
#Mann= 5 ,-1 , 0
       0    .035       0   395.6    .045       0   429.3    .035       0
     510     .04       0  733.78      .1       0
Bank Sta=395.6,429.3
XS Rating Curve= 0 ,0
Exp/Cntr=0.3,0.1

Type RM Length L Ch R = 1 ,12382   ,202.7,193.3,183.4
XS GIS Cut Line= 3
     1995995.699      173776.3281995715.82708689173109.532172088
1995549.45509364173047.467434765
#Sta/Elev= 30
       0 1596.92    53.6 1569.74    67.8 1567.78    81.4 1564.17   116.5  1560.6
   161.6 1558.08   231.5 1558.44   274.4 1557.25   372.1 1556.82   380.9 1556.53
   386.71555.264   395.1 1553.56     419 1553.75     4271556.937   500.5 1558.86
   679.8 1558.95   711.8 1560.77     718 1561.95   727.1 1565.96   730.8 1566.59
     751 1567.01   763.9 1580.47   776.5 1591.37   779.1 1594.35   786.7 1605.73
   797.4 1615.88   824.7    1638   846.1 1657.36   863.6  1669.2   900.7 1702.27
#Mann= 5 ,-1 , 0
       0    .035       0   386.7    .045       0     427    .035       0
  753.15     .04       0  783.15      .1       0
Bank Sta=386.7,427
XS Rating Curve= 0 ,0
Exp/Cntr=0.3,0.1

Type RM Length L Ch R = 1 ,12189   ,226.3,223.6,214.7
XS GIS Cut Line= 4
1996209.14911844173416.2454333961996110.58423545173407.167088909
1995713.73089076173064.7838111361995590.52478701173010.313744218
#Sta/Elev= 30
       0 1620.79    44.6 1593.36    57.6 1586.96    67.5 1580.54   110.6 1561.92
   139.9 1558.15   165.9 1556.86   217.2 1557.15   226.5 1554.53   235.2 1553.53
   256.9  1554.2   267.4 1556.02   282.7 1556.68   332.7 1556.72   347.8 1556.22
   357.8 1554.63   373.4 1557.06   443.2 1556.87   555.9 1558.92   586.2  1561.4
   603.7  1566.6   622.3 1567.52   625.1 1569.13   635.6 1580.86   646.4 1589.72
   667.9    1613   705.7 1645.28   718.1 1656.96     736 1669.17   757.8 1688.87
#Mann= 10 ,-1 , 0
       0      .1       0      60    .035       0  118.98      .1       0
  178.98    .035       0   226.5    .045       0   256.9    .035       0
  418.98      .1       0  568.98    .035       0  578.98     .04       0
  683.12      .1       0
Bank Sta=226.5,256.9
XS Rating Curve= 0 ,0
Exp/Cntr(USF)=0,0
Exp/Cntr=0.3,0.1

Type RM Length L Ch R = 1 ,11965   ,172.9,192.7,207.9
XS GIS Cut Line= 3
1996207.49565546173231.7767439831996099.70841477 173142.09429517
     1995650.551      172933.273
#Sta/Elev= 30
       0 1612.78      17 1603.73    42.6 1594.05    59.7 1585.27    68.2 1582.91
      81 1575.13    93.8 1573.71   110.9 1562.68   116.6 1560.49   119.4 1559.95
   128.3 1562.01   140.7 1556.54   147.9  1555.2   206.6 1556.37     224 1555.05
   230.7 1552.96   234.7 1551.73   265.8 1552.86   275.7 1556.89   339.9 1556.41
   453.5 1557.95   483.2  1560.3     488 1562.74   498.9 1571.31   517.8 1571.41
   524.2 1577.02   538.7 1592.92   571.2 1615.52   622.9 1658.89   635.5 1667.57
#Mann= 5 ,-1 , 0
       0      .1       0   230.7    .045       0   265.8      .1       0
  480.22     .04       0  630.22      .1       0
#XS Ineff= 2 , 0
          128.17 1565.33
Permanent Ineff=
       F       F
Bank Sta=230.7,265.8
XS Rating Curve= 0 ,0
Exp/Cntr=0.3,0.1

Type RM Length L Ch R = 1 ,11773   ,144.3,152.4,158.4
XS GIS Cut Line= 3
1996234.95172568173172.0124019951996197.33966057173074.001908918
     1995961.594      172633.465
#Sta/Elev= 30
       0  1616.9    69.1  1585.9    80.3 1578.55    90.9 1577.11    94.4 1574.53
   101.4  1567.4   103.9 1565.86   114.4 1563.42   127.2 1556.41     141 1554.87
   166.7    1556   177.8 1554.91   197.9 1554.63   206.5 1552.06   212.8 1551.04
   233.1  1551.2   238.9 1552.13   245.2 1555.53     250  1556.5   288.9  1556.9
   413.8 1561.45   439.8 1563.44   462.1 1563.28   482.8 1564.82   521.7 1565.04
   532.8 1566.38     544  1566.1   555.2 1568.66   573.8 1578.73   604.6 1601.46
#Mann= 3 ,-1 , 0
       0      .1       0   206.5    .045       0   238.9      .1       0
Bank Sta=206.5,238.9
XS Rating Curve= 0 ,0
Exp/Cntr=0.3,0.1

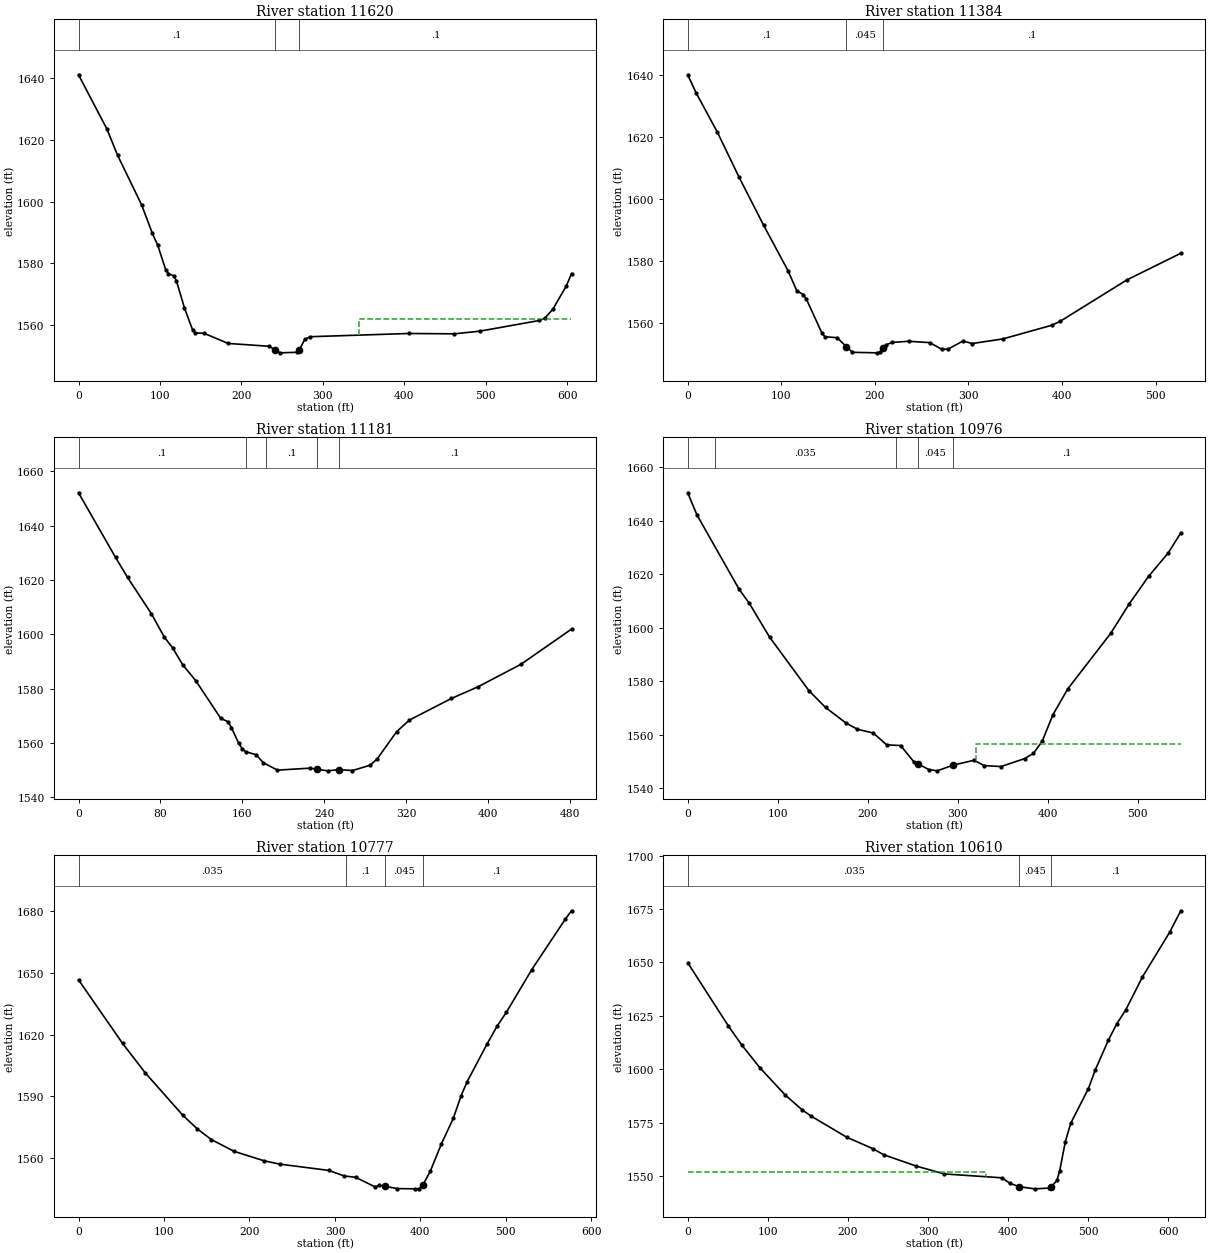
Type RM Length L Ch R = 1 ,11620   ,227.9,235.9,238.7
XS GIS Cut Line= 4
1996316.47436898173171.1332082611996308.74323579173036.384433145
1996224.36263258172648.9737718431996227.47473829172575.334888903
#Sta/Elev= 30
       0 1640.94    34.8 1623.46    47.9 1614.97    77.5 1598.89    90.7 1589.69
    97.2 1585.91   107.1 1577.92   110.4 1576.71     117    1576   120.2 1574.37
   130.1 1565.57   140.1  1558.5   143.4  1557.5   153.5 1557.49   183.7 1554.16
   234.1 1553.24   240.9 1552.12   247.5 1551.12   267.7  1551.3   271.21552.114
   277.7 1555.46   284.5 1556.33   405.3 1557.37   461.3 1557.26   492.6 1558.12
   565.7 1561.57   572.3 1562.31   582.2 1565.19   598.6 1572.64   605.2 1576.72
#Mann= 3 ,-1 , 0
       0      .1       0   240.9    .045       0   271.2      .1       0
#XS Ineff= 1 ,-1
  344.28   604.4 1562.16
Permanent Ineff=
       F
Bank Sta=240.9,271.2
XS Rating Curve= 0 ,0
Exp/Cntr=0.3,0.1

Type RM Length L Ch R = 1 ,11384   ,194.9,203.3,210.7
XS GIS Cut Line= 3
1996472.09055863173197.6640683581996477.64516632172833.875301894
1996597.37956394 172722.97390286
#Sta/Elev= 30
       0 1640.07     8.8 1634.34    31.8 1621.51    54.7 1607.18      81 1591.65
   107.2 1576.94   116.5 1570.53   123.6 1569.22   126.9 1567.74   143.3 1556.95
   146.6 1555.65   159.7 1555.35   169.6 1552.44   176.1 1550.64   202.4 1550.47
   205.7 1550.73   208.9 1551.93   212.2  1553.1   218.8 1553.83   236.1  1554.2
   258.7 1553.76   271.3 1551.66   277.8  1551.6   294.2 1554.28   304.1 1553.47
   336.9 1554.96   389.2 1559.36   398.2 1560.64   469.4 1573.97     527 1582.55
#Mann= 3 ,-1 , 0
       0      .1       0   169.6    .045       0   208.9      .1       0
Bank Sta=169.6,208.9
XS Rating Curve= 0 ,0
Exp/Cntr=0.3,0.1

Type RM Length L Ch R = 1 ,11181   ,202.1,204.8,205.5
XS GIS Cut Line= 4
1996564.20033682173251.8399203481996627.16713095173170.094899945
1996700.01979315172960.3807239731996817.58312369172857.885302578
#Sta/Elev= 30
       0 1652.06    36.2 1628.24    47.9 1620.88    71.2 1607.49    83.6    1599
    91.9 1594.93   101.7 1588.73   114.6 1582.79   138.9 1568.96   145.8 1567.82
   149.3 1565.56   156.2 1559.95   159.7 1557.85   163.2 1556.74   173.3 1555.64
   180.5 1552.64   194.2 1549.95   225.7 1550.68   232.6 1550.29   243.1 1549.69
   254.2 1550.15   267.4 1549.81   284.7 1551.76   291.7 1554.18   310.4 1564.07
   322.9 1568.37   363.9 1576.33     390 1580.65   431.8 1588.91   481.2 1601.88
#Mann= 5 ,-1 , 0
       0      .1       0  163.18    .035       0  183.18      .1       0
   232.6    .045       0   254.2      .1       0
Bank Sta=232.6,254.2
XS Rating Curve= 0 ,0
Exp/Cntr=0.3,0.1

Type RM Length L Ch R = 1 ,10976   ,182.4,199.4,207.7
XS GIS Cut Line= 4
1996622.53569182173319.0387561251996792.28316422173231.817608662
1996892.52037692 173047.412100511997013.83102027 172964.50434311
#Sta/Elev= 30
       0 1650.46    10.2 1642.22    57.2  1614.3    68.3 1609.18      91 1596.45
   134.7 1576.43   153.1 1570.17   175.9 1564.33   188.5 1562.02   206.1 1560.63
     221 1556.19   236.5 1555.93   251.1 1549.87   255.8 1549.03   267.9 1546.96
   277.1 1546.47   294.5 1548.57   318.1 1550.43   329.3 1548.42     348 1548.08
   374.4 1551.06   384.1 1553.04   393.7 1557.48   405.7 1567.45   422.2 1577.13
   469.8 1597.85   490.7 1609.04   511.9 1619.18   533.8 1627.97   547.7 1635.46
#Mann= 5 ,-1 , 0
       0      .1       0      30    .035       0  230.84      .1       0
   255.8    .045       0   294.5      .1       0
#XS Ineff= 2 , 0
                          319.77         1556.58
Permanent Ineff=
       F       F
Bank Sta=255.8,294.5
XS Rating Curve= 0 ,0
Exp/Cntr=0.3,0.1

Type RM Length L Ch R = 1 ,10777   ,153.1,167.1,176.7
XS GIS Cut Line= 3
1996662.19854577173397.8732592681996870.46504219173356.186786729
1997152.35978921173125.295001275
#Sta/Elev= 30
       0 1646.71    51.6 1615.78    78.3 1601.38   121.9 1580.93   138.6 1574.35
   155.3 1569.06   182.1  1563.3   216.9 1558.74   235.6 1557.09   292.8 1554.04
   310.7 1551.34   324.2 1550.68     347 1546.03   352.1 1546.75   359.1 1546.26
   373.1  1545.2   394.1 1545.08   398.8 1545.13     403 1547.03   411.5 1553.61
   424.4  1566.8   438.4 1579.31   447.7 1590.47   454.7 1597.22     478 1615.56
   489.7  1624.2   500.6 1630.95   530.2 1651.65   569.6 1676.31   576.8 1680.31
#Mann= 4 ,-1 , 0
       0    .035       0   312.4      .1       0   359.1    .045       0
     403      .1       0
Bank Sta=359.1,403
XS Rating Curve= 0 ,0
Exp/Cntr=0.3,0.1

Type RM Length L Ch R = 1 ,10610   ,216.4,229.1,240.1
XS GIS Cut Line= 4
1996661.88291894 173449.790322161996910.44033639173443.718896439
1997144.08903868173370.660600146 1997235.0520077173289.329588396
#Sta/Elev= 30
       0 1649.82    50.9 1620.19    67.4  1611.4    90.3 1600.63   121.9 1587.91
   142.8 1581.07   153.9 1578.15   198.6 1568.23   231.4 1562.84   244.6 1560.05
   285.6 1554.72     320 1551.08   392.2 1549.26   402.5  1546.6   414.1 1545.08
   433.4  1544.1   450.6 1544.45   454.1 1545.15   460.9 1548.02   464.4  1552.6
   471.3 1565.98   478.1 1574.76   500.2 1590.97     509 1599.91     525 1613.52
   535.5 1621.22   546.8 1627.77   567.7 1643.23   601.5 1664.02   615.5 1674.15
#Mann= 3 ,-1 , 0
       0    .035       0   414.1    .045       0   454.1      .1       0
#XS Ineff= 2 , 0
             372    1552
Permanent Ineff=
       F       F
Bank Sta=414.1,454.1
XS Rating Curve= 0 ,0
Exp/Cntr=0.3,0.1