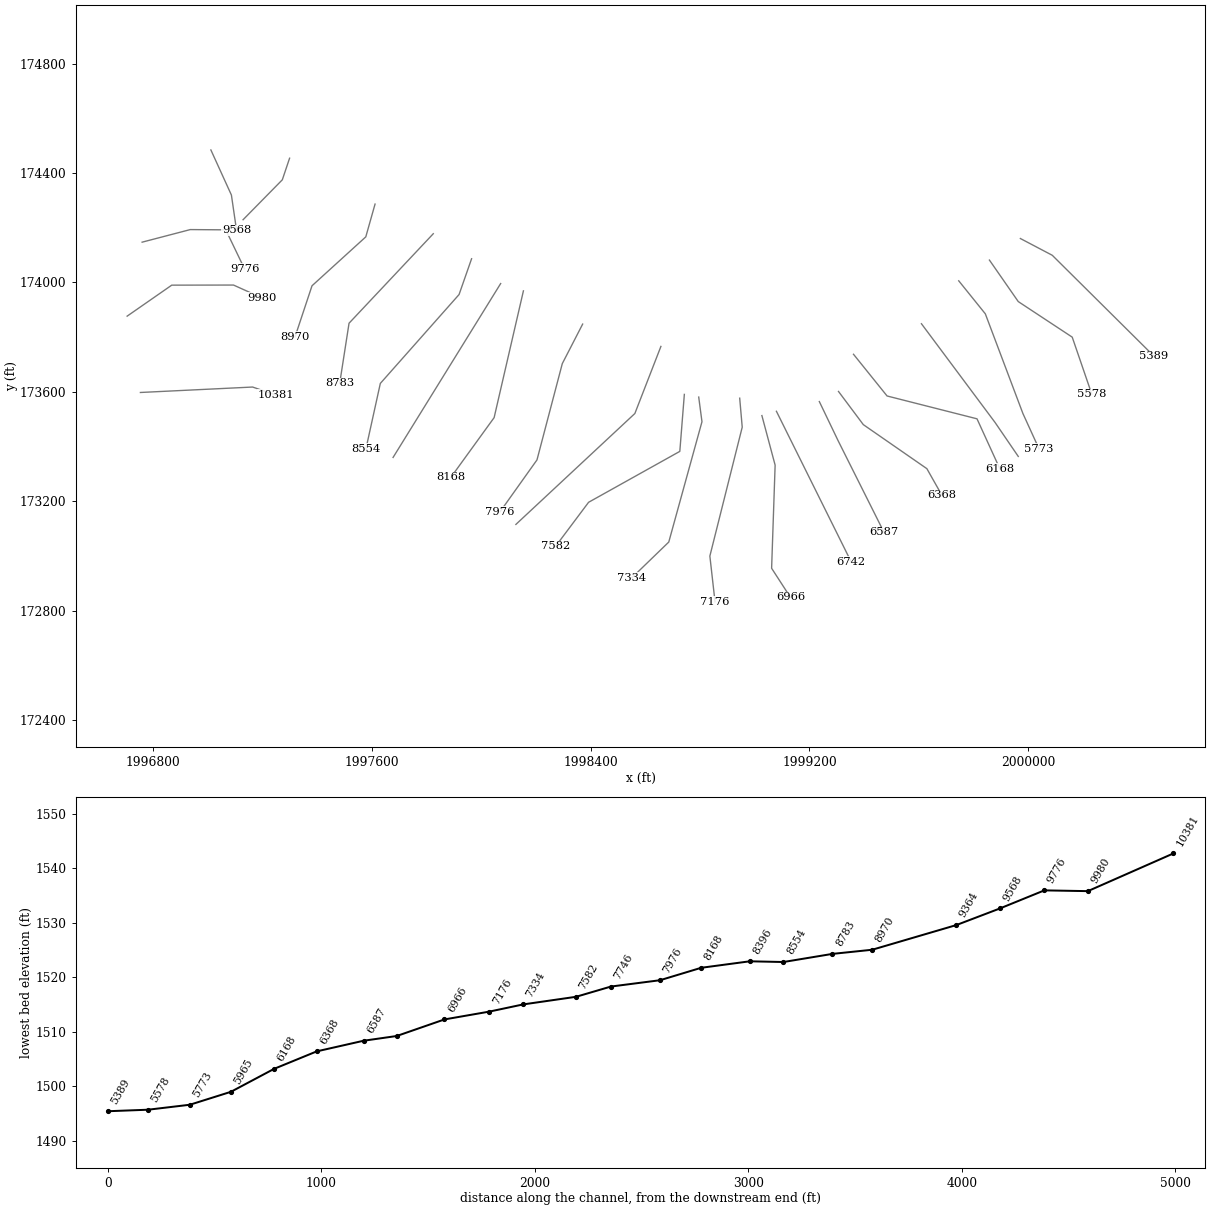
HEC-RAS study LICKCK.prj: LICKCK

--- LICKCK.g01 (geometry) --- (continued)

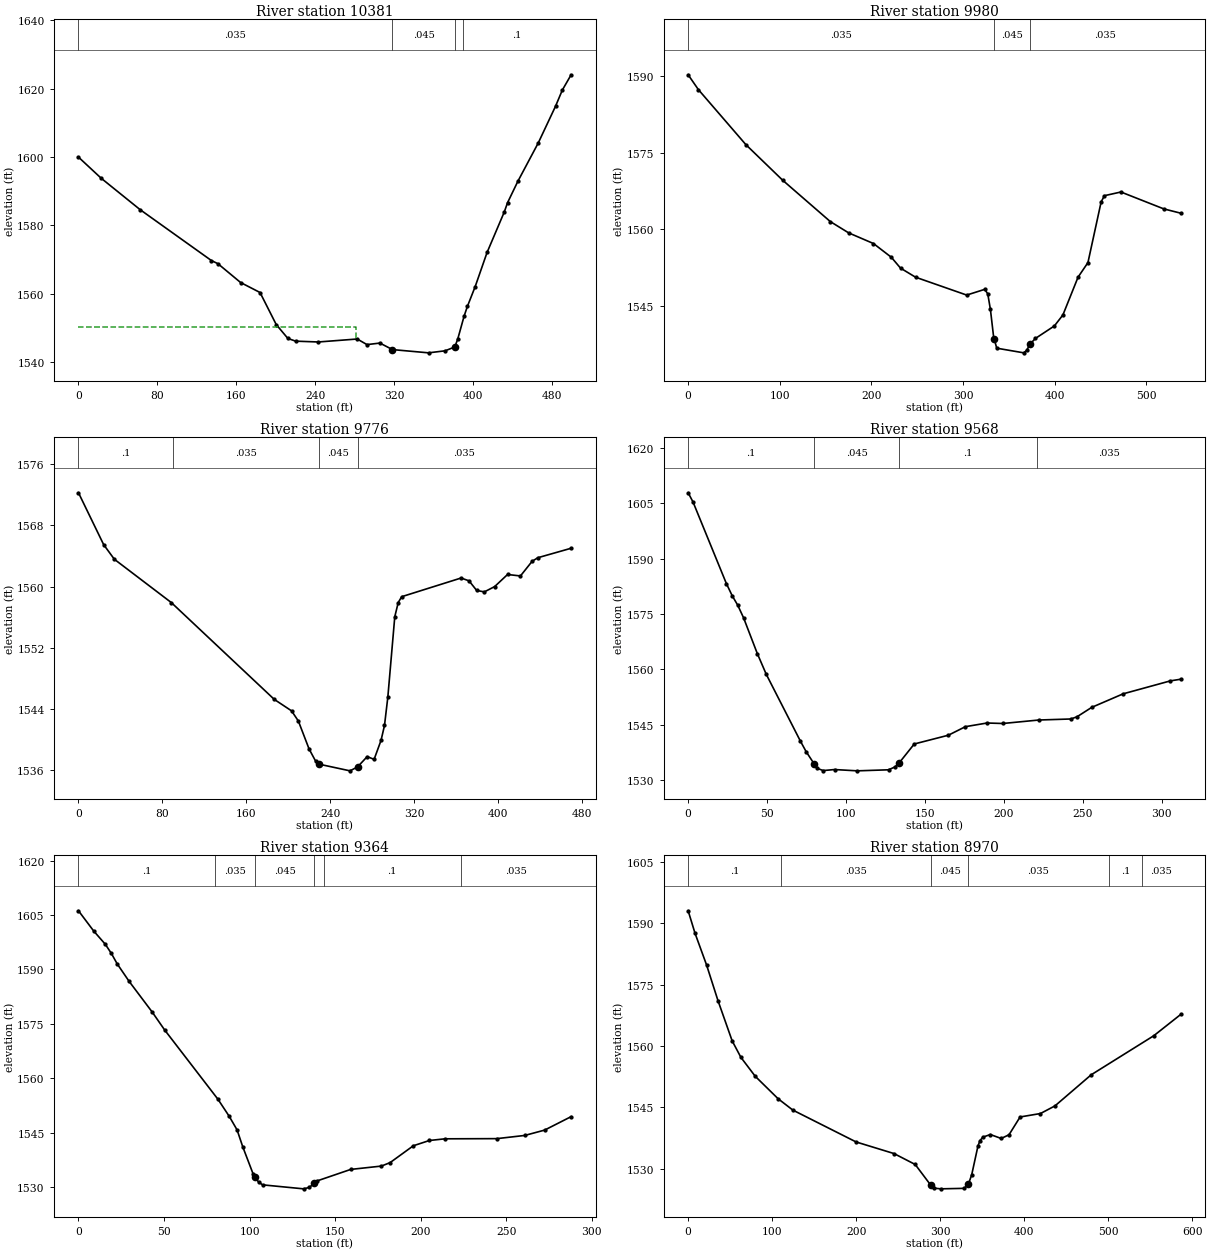
Type RM Length L Ch R = 1 ,10381   ,398.7,400.9,401.7
XS GIS Cut Line= 3
1996755.39961076173597.1711823941997165.27985814173617.058541579
1997249.51504562 173588.37343546
#Sta/Elev= 30
       0 1599.99    23.1 1593.79    62.5 1584.61   134.7 1569.72   141.3  1568.8
   164.3 1563.29     184 1560.36   200.4 1550.99   212.2 1546.92   220.1 1546.12
   243.1 1545.88   282.5 1546.75   292.4 1545.11   305.5 1545.56   318.2 1543.65
   354.8  1542.7   371.5 1543.29   381.4 1544.42   384.4 1546.75   390.9 1553.51
   394.2 1556.31   402.1 1562.12   414.1 1572.08   431.5  1583.9   434.9 1586.67
   445.3 1592.91     466 1604.15   483.5 1614.89   490.4 1619.63   499.3  1624.1
#Mann= 4 ,-1 , 0
       0    .035       0   318.2    .045       0   381.4    .035       0
     390      .1       0
#XS Ineff= 2 , 0
          281.41  1550.3
Permanent Ineff=
       F       F
Bank Sta=318.2,381.4
XS Rating Curve= 0 ,0
Exp/Cntr=0.3,0.1

Type RM Length L Ch R = 1 ,9980    ,203.9,203.9,204.1
XS GIS Cut Line= 4
1996706.91407061  173876.24847041996869.90032798173989.608353668
1997095.58142486173989.9611034731997198.80574218173943.371596231
#Sta/Elev= 30
       0 1590.22    11.2 1587.31    63.1 1576.52   103.1 1569.58   155.1 1561.48
   175.1 1559.27   202.2 1557.18   221.7 1554.49   231.7 1552.37   248.1 1550.59
   303.9 1547.09   323.6 1548.21   326.9 1547.33   329.8 1544.27   333.4 1538.71
   333.9 1538.51   336.7 1536.69   366.2 1535.78   369.5 1536.29   372.8 1537.45
   378.9  1538.6   399.6 1541.05   408.9  1543.2   425.4 1550.59   436.2 1553.45
   450.6 1565.33   454.2 1566.55   472.2 1567.27     519 1563.96   537.5 1563.12
#Mann= 3 ,-1 , 0
       0    .035       0   333.9    .045       0   372.8    .035       0
Bank Sta=333.9,372.8
XS Rating Curve= 0 ,0
Exp/Cntr=0.3,0.1

Type RM Length L Ch R = 1 ,9776    ,246.2,208.3,167.7
XS GIS Cut Line= 4
1996761.72927539174146.7787952221996937.62765987174192.790349315
1997067.31857085      174191.848 1997135.7303618 174049.36511969
#Sta/Elev= 30
       0 1572.26      24 1565.48    34.2 1563.57    88.5 1557.91   186.6 1545.26
   203.1 1543.76   209.6 1542.43   219.8 1538.78     226  1537.2   229.7 1536.78
   258.8 1535.92     266 1536.43   275.2 1537.78   281.8 1537.42   288.4  1539.9
   291.7 1541.85   294.9 1545.58   301.5 1556.06   304.8 1557.92   308.1 1558.68
   364.7 1561.12   372.3 1560.75   379.6 1559.49   386.9 1559.31   396.7    1560
     409 1561.58   421.3 1561.39   432.4  1563.3   437.8 1563.77   469.6 1565.01
#Mann= 4 ,-1 , 0
       0      .1       0      90    .035       0   229.7    .045       0
     266    .035       0
Bank Sta=229.7,266
XS Rating Curve= 0 ,0
Exp/Cntr=0.3,0.1

Type RM Length L Ch R = 1 ,9568    ,241.8,203.6,165.2
XS GIS Cut Line= 3
1997012.90486581174483.9090054441997087.87532192174319.081130137
1997106.74802823174189.486925175
#Sta/Elev= 30
       0 1607.77     3.1 1605.27    24.2 1583.24    27.9 1579.94    31.4 1577.38
    35.1 1573.97    43.8 1564.31    49.5 1558.67    71.1 1540.63    74.7 1537.81
    79.9 1534.42    81.9 1533.26    85.5 1532.67    92.7 1532.95   107.1  1532.6
   126.9 1532.88     131 1533.66   133.5 1534.67   143.2 1539.86   164.8 1542.23
   175.6 1544.54   189.3 1545.53   199.3  1545.4   222.1 1546.34   242.4 1546.62
   246.3 1547.22   255.6 1549.76   275.5 1553.42   305.4 1556.92     312 1557.37
#Mann= 4 ,-1 , 0
       0      .1       0    79.9    .045       0   133.5      .1       0
  221.08    .035       0
Bank Sta=79.9,133.5
XS Rating Curve= 0 ,0
Exp/Cntr=0.3,0.1

Type RM Length L Ch R = 1 ,9364    ,391.6,394.4,392.8
XS GIS Cut Line= 3
1997300.46720252174453.7640119551997273.90109339174374.823429436
1997130.49515379174228.829702275
#Sta/Elev= 30
       0 1606.16     8.8 1600.64    15.7 1596.92    19.2 1594.42    22.6 1591.55
    29.6 1586.71    43.1 1578.25    50.3 1573.36    81.5 1554.24    88.1 1549.53
    92.7 1545.78      96 1541.14   102.1 1533.61     103 1532.76   105.3 1531.42
   107.6 1530.66   131.5 1529.56   134.9 1529.95   137.8  1531.1   139.6 1531.77
   159.1 1534.91     177 1535.83   182.1 1536.78   195.7 1541.43   205.1 1542.88
   214.2 1543.34   244.5 1543.39   260.8 1544.27   272.4 1545.74   287.9 1549.45
#Mann= 6 ,-1 , 0
       0      .1       0      80    .035       0     103    .045       0
   137.8    .035       0  143.29      .1       0  223.29    .035       0
Bank Sta=103,137.8
XS Rating Curve= 0 ,0
Exp/Cntr=0.3,0.1

Type RM Length L Ch R = 1 ,8970    ,183.8,186.3,188.8
XS GIS Cut Line= 4
1997612.71602085174286.0279414771997578.87772852174166.155877161
1997382.36857799173987.2973710721997320.61369039173801.365905679
#Sta/Elev= 30
       0 1593.08     8.2 1587.57    21.9 1579.83    35.5 1571.09    52.4 1561.23
    62.8  1557.2    79.8 1552.58   107.1 1547.07   124.6  1544.3   199.9  1536.5
     245 1533.66   270.2 1530.99   288.6 1525.95     293 1525.19   300.7 1525.03
   328.5 1525.15   333.5 1526.18   337.4 1528.46   344.8 1535.46   347.2 1536.82
   350.7 1537.68   359.6 1538.32   372.5 1537.36   381.8 1538.26     395 1542.62
   419.2 1543.46   436.5 1545.33   479.6 1552.94     554 1562.49   586.2 1567.72
#Mann= 6 ,-1 , 0
       0      .1       0     110    .035       0   288.6    .045       0
   333.5    .035       0  500.27      .1       0  540.27    .035       0
Bank Sta=288.6,333.5
XS Rating Curve= 0 ,0
Exp/Cntr=0.3,0.1

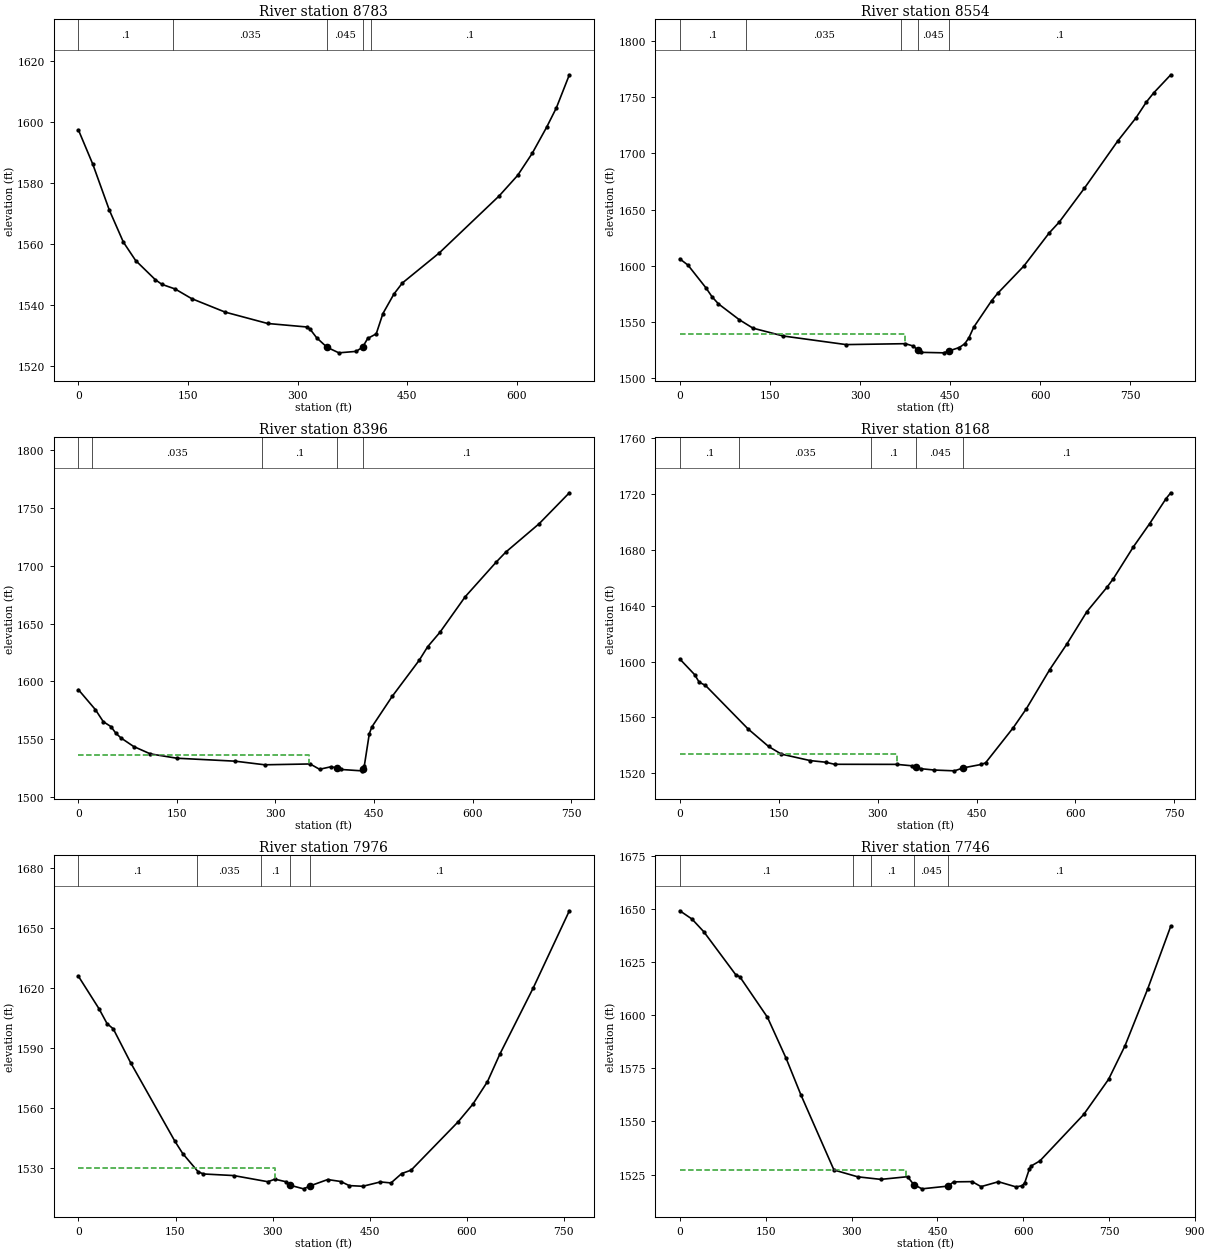
Type RM Length L Ch R = 1 ,8783    ,229,229.5,231.3
XS GIS Cut Line= 3
1997825.45356438      174177.6611997517.69431602173850.427316024
1997483.55260982 173630.72474928
#Sta/Elev= 30
       0 1597.33    19.7 1586.08    42.3 1571.05    61.5 1560.56    78.3 1554.52
   105.3 1548.22   114.3  1546.7   132.3  1545.2   154.8 1542.05   200.8 1537.61
   258.8 1533.89   312.2 1532.75     317    1532     326 1529.19   340.1 1526.09
   356.3 1524.27     380 1524.75   388.8 1526.15   395.8    1529   407.4 1530.49
   416.6 1537.16   431.6 1543.53   443.1 1547.14   493.7 1557.02   575.6  1575.7
   600.8  1582.4   620.7 1589.61   640.6 1598.24   653.9 1604.59   671.6 1615.39
#Mann= 5 ,-1 , 0
       0      .1       0     130    .035       0   340.1    .045       0
   388.8    .035       0     400      .1       0
Bank Sta=340.1,388.8
XS Rating Curve= 0 ,0
Exp/Cntr=0.3,0.1

Type RM Length L Ch R = 1 ,8554    ,152.5,157.7,163.4
XS GIS Cut Line= 4
1997965.42262086174086.1654844571997919.67461763173955.295715555
1997631.98701002173630.2913991841997579.42728385173391.424179549
#Sta/Elev= 30
       0  1606.2    13.6 1600.66    43.4 1580.54    53.8 1572.44    64.3 1566.25
      99 1552.19   121.8 1544.68   172.2 1537.72   276.8  1530.1   375.5 1530.91
   388.4 1528.85   396.3  1525.3   402.3 1523.21   439.5 1522.78     448 1524.45
   465.1 1527.48   474.4 1530.83   481.4 1536.27   489.3 1545.56     519 1569.02
   528.9 1575.47   572.7 1599.82   614.8 1629.16   631.6 1638.85   673.4 1668.85
     729 1710.83   759.3 1731.34   776.7 1745.49   788.9 1753.59   817.3 1769.65
#Mann= 5 ,-1 , 0
       0      .1       0     110    .035       0  368.64      .1       0
   396.3    .045       0     448      .1       0
#XS Ineff= 2 , 0
          374.08  1539.2
Permanent Ineff=
       F       F
Bank Sta=396.3,448
XS Rating Curve= 0 ,0
Exp/Cntr=0.3,0.1

Type RM Length L Ch R = 1 ,8396    ,215.4,227.6,236.3
XS GIS Cut Line= 2
     1998071.615      173995.4221997678.58789468173359.671116359
#Sta/Elev= 30
       0 1592.93      26 1575.61    37.9 1565.31    49.5 1561.09    57.2 1555.24
    64.9 1551.25    84.2 1543.88   109.6 1537.52   149.8  1533.8   238.5 1531.25
   283.6 1528.13   352.8 1528.84   367.1 1524.25   383.8 1526.34   393.3  1525.6
   400.4 1524.07   431.1 1522.91   433.8  1524.6   435.2 1526.95   442.9 1555.04
   446.8 1560.84   477.6 1587.07   518.9 1618.34   531.6 1629.89   550.6 1642.58
   588.7 1672.99   636.4  1703.2   650.7 1711.63   701.4 1736.08   747.4 1762.77
#Mann= 5 ,-1 , 0
       0      .1       0      20    .035       0     280      .1       0
   393.3    .045       0   433.8      .1       0
#XS Ineff= 2 , 0
           351.1 1536.18
Permanent Ineff=
       F       F
Bank Sta=393.3,433.8
XS Rating Curve= 0 ,0
Exp/Cntr=0.3,0.1

Type RM Length L Ch R = 1 ,8168    ,196.6,192.8,192.4
XS GIS Cut Line= 3
     1998154.793      173968.7351998047.76413419173505.203386523
1997890.17811534173287.465369119
#Sta/Elev= 30
       0 1601.78    22.6 1590.53    29.3 1585.21    38.9 1582.89   103.4 1551.77
   134.6 1539.17   153.9 1533.71   197.8 1529.05   221.2  1527.9   234.7 1526.41
     329 1526.35   352.5 1525.31   358.9 1524.28     366 1523.23   386.2 1522.28
   416.5 1521.72   429.9 1523.85   456.9 1526.28   463.7 1527.48   505.8 1552.71
   525.5 1566.17     561 1594.26   586.8  1612.4   617.4 1635.78     648 1653.29
   657.4 1659.29   687.9 1682.16   712.3 1698.58   737.2 1716.54   744.5 1720.81
#Mann= 5 ,-1 , 0
       0      .1       0      90    .035       0     290      .1       0
   358.9    .045       0   429.9      .1       0
#XS Ineff= 2 , 0
          329.92 1533.92
Permanent Ineff=
       F       F
Bank Sta=358.9,429.9
XS Rating Curve= 0 ,0
Exp/Cntr=0.3,0.1

Type RM Length L Ch R = 1 ,7976    ,245.2,229.9,210.9
XS GIS Cut Line= 4
1998371.22721063173847.1761364021998296.82708306173702.674724557
1998204.34551554173350.6349147271998069.89991575173161.663210634
#Sta/Elev= 30
       0  1625.7    31.9 1609.41    44.2 1602.04    53.9 1599.37    80.7 1582.47
   148.9 1543.32   161.1 1537.09   184.9 1527.99   193.2 1526.87   239.8 1526.08
   292.6    1523   303.7 1524.25   320.6 1522.99   327.5  1521.2   347.8 1519.44
   357.9 1520.92   385.1 1524.08   405.4  1523.1   418.3 1521.06   439.3 1520.72
   466.5 1522.89   482.9 1522.39   499.4 1527.08     514 1528.78   586.6 1552.94
   609.3 1561.74   631.9 1573.02     651 1586.74   702.8 1619.97   758.4  1658.4
#Mann= 5 ,-1 , 0
       0      .1       0  182.53    .035       0  282.53      .1       0
   327.5    .045       0   357.9      .1       0
#XS Ineff= 2 , 0
          303.77 1529.75
Permanent Ineff=
       F       F
Bank Sta=327.5,357.9
XS Rating Curve= 0 ,0
Exp/Cntr=0.3,0.1

Type RM Length L Ch R = 1 ,7746    ,170.8,163.5,154.5
XS GIS Cut Line= 3
     1998657.111       173765.561998561.97366401173520.282989978
     1998127.307      173114.776
#Sta/Elev= 30
       0 1649.03    21.3 1645.13    41.9 1639.17    97.7 1618.95   104.8    1618
   153.1 1598.93   185.7 1579.63   211.4 1562.53   269.2 1527.15   310.8 1523.93
   351.1 1522.73   397.8 1523.99   408.5 1520.32   422.9 1518.28   468.8 1519.58
   478.1 1521.56   510.6 1521.67   526.1 1519.32   556.5 1521.62   587.2 1519.19
   597.9 1519.76   602.4 1521.11   610.4 1527.54   614.2  1529.1     629 1531.43
   705.4 1553.24   748.9 1569.79   777.6 1585.58     817 1612.15   857.5  1641.8
#Mann= 5 ,-1 , 0
       0      .1       0  303.08    .035       0  333.08      .1       0
   408.5    .045       0   468.8      .1       0
#XS Ineff= 2 , 0
          394.93 1527.34
Permanent Ineff=
       F       F
Bank Sta=408.5,468.8
XS Rating Curve= 0 ,0
Exp/Cntr=0.3,0.1

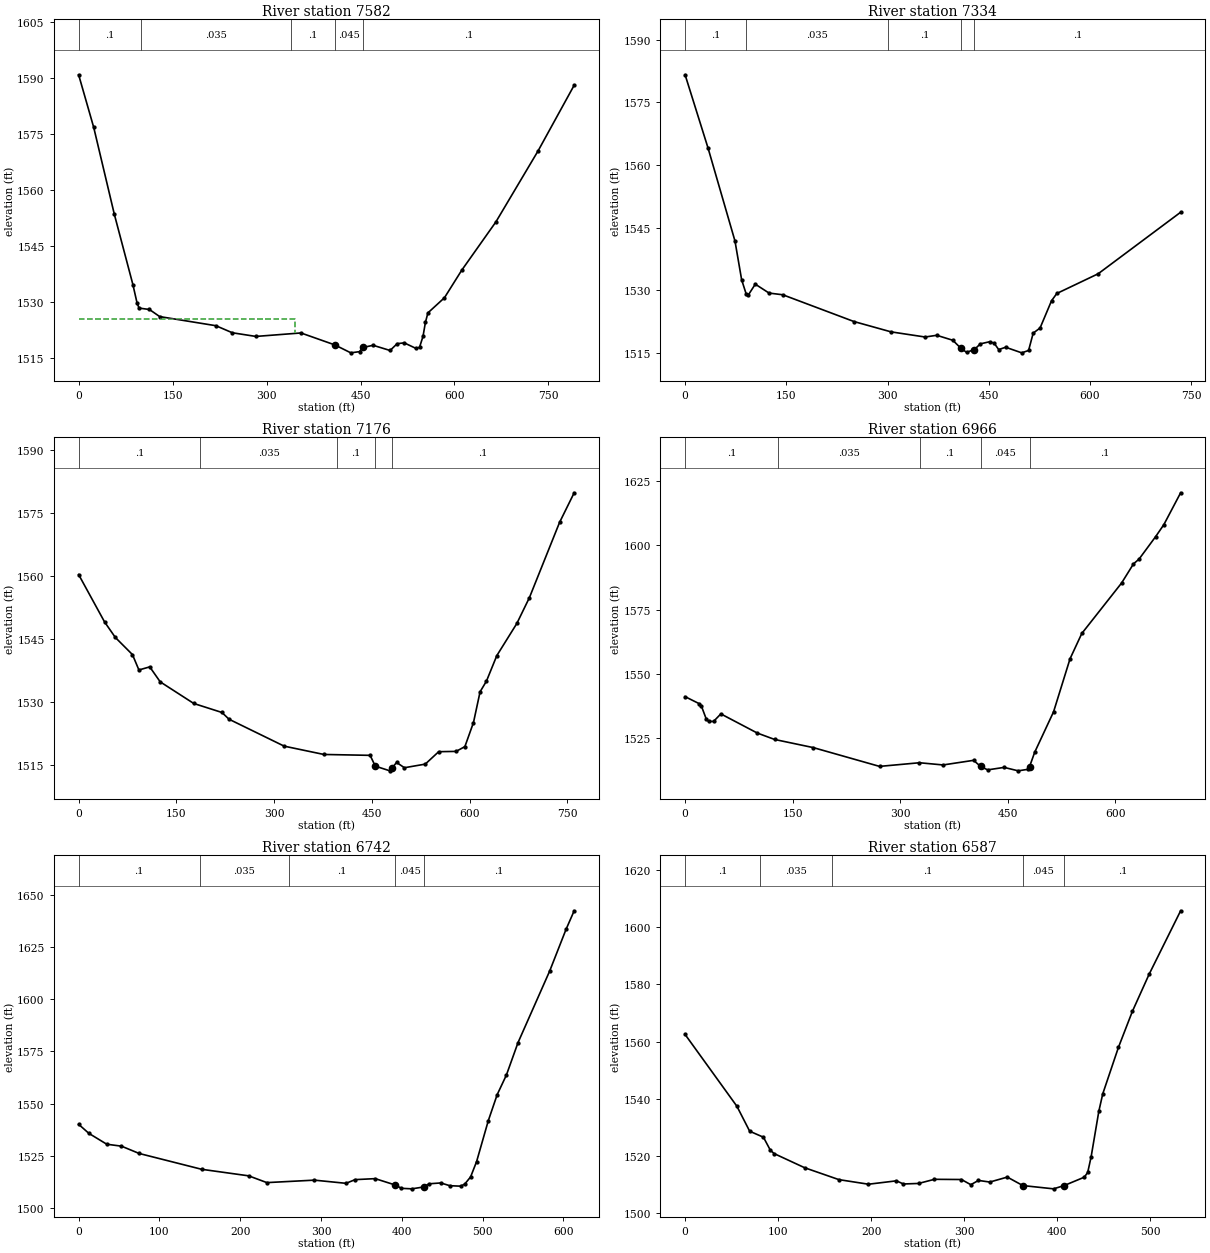
Type RM Length L Ch R = 1 ,7582    ,215.6,248.1,264.5
XS GIS Cut Line= 4
1998742.76515747      173590.1931998726.20338016173381.796348056
1998392.89422049173195.6537214971998272.84928487173035.333599796
#Sta/Elev= 30
       0  1590.8    24.1 1576.71      57 1553.47    86.6 1534.68    93.2 1529.79
    96.5 1528.37     113    1528   129.4  1526.1   219.1 1523.66   245.4 1521.77
     283 1520.79   354.9 1521.72     4091518.522   434.5  1516.4   448.4 1516.72
   453.7 1517.83   470.1 1518.42   497.2 1517.03   508.5 1518.85   519.8 1519.07
   538.5 1517.59   544.2 1517.87   549.8 1520.82   553.6 1524.53   557.6 1527.09
     584 1531.14   611.6 1538.51   666.2 1551.45   733.6 1570.47   791.1    1588
#Mann= 5 ,-1 , 0
       0      .1       0     100    .035       0  339.05      .1       0
     409    .045       0   453.7      .1       0
#XS Ineff= 2 , 0
          346.14 1525.49
Permanent Ineff=
       F       F
Bank Sta=409,453.7
XS Rating Curve= 0 ,0
Exp/Cntr=0.3,0.1

Type RM Length L Ch R = 1 ,7334    ,156.3,158.5,158.2
XS GIS Cut Line= 4
1998795.26556686173580.3420200751998807.15493048173490.178308328
1998685.87194148173050.2747607981998551.48958693172920.196102081
#Sta/Elev= 30
       0 1581.57    34.1 1563.98    73.9 1541.78    83.8 1532.48    90.4 1529.15
    93.8 1528.88     104 1531.44   124.4 1529.31   144.8  1528.9   250.3 1522.49
   305.2 1520.02   355.6 1518.79   372.9  1519.2   396.7 1518.01   408.71516.088
   417.1 1515.12   428.71515.792   437.5 1517.15   451.1 1517.65   457.9 1517.33
   464.7 1515.78     475 1516.34   498.8    1515     509 1515.57   515.8 1519.72
     526 1520.95     543 1527.47   550.8 1529.21   612.1 1533.93   734.3 1548.66
#Mann= 5 ,-1 , 0
       0      .1       0      90    .035       0  300.94      .1       0
   408.7    .045       0   428.7      .1       0
Bank Sta=408.7,428.7
XS Rating Curve= 0 ,0
Exp/Cntr=0.3,0.1

Type RM Length L Ch R = 1 ,7176    ,201.4,209.6,218.3
XS GIS Cut Line= 4
1998945.00246989173576.3301388251998954.22411115173470.335641093
1998836.00246989172999.0409965931998854.83276932172831.994610415
#Sta/Elev= 30
       0 1560.42    39.8 1549.14    56.3 1545.45    82.6 1541.36    92.5  1537.7
   109.1 1538.44   125.2 1534.87   176.7 1529.72   219.9 1527.58   230.8 1525.97
   315.4 1519.56   376.3 1517.58   447.3 1517.37   455.2  1514.8   477.7 1513.68
   481.1 1514.39   487.9 1515.68   499.9 1514.42   531.9 1515.28   552.5 1518.24
   579.2 1518.31   592.7 1519.45   605.9 1525.19     616  1532.5   625.8 1535.05
   641.7 1541.12   672.4 1548.77   691.8 1554.96     738 1572.85   760.4  1579.9
#Mann= 5 ,-1 , 0
       0      .1       0  186.39    .035       0  396.39      .1       0
   455.2    .045       0   481.1      .1       0
Bank Sta=455.2,481.1
XS Rating Curve= 0 ,0
Exp/Cntr=0.3,0.1

Type RM Length L Ch R = 1 ,6966    ,201.1,223.6,245.9
XS GIS Cut Line= 4
     1999026.099      173512.7021999074.44733028173331.436970452
1999061.60795737172954.4262929971999130.39859034172848.159789391
#Sta/Elev= 30
       0 1541.12    19.4 1538.43    22.8 1537.42    29.5 1532.43    32.9 1531.47
    39.7 1531.48    49.9 1534.41   100.7 1526.96   124.9 1524.46   178.9 1521.29
   271.3 1513.98     327  1515.4   359.9 1514.54   402.5 1516.34   412.3 1513.95
   422.2 1512.63   445.1 1513.59   464.8 1512.25     478 1512.83   480.6 1513.88
   487.8  1519.5   514.1 1535.22   537.1 1555.87   553.5 1565.71     609 1585.34
   625.6 1592.79   633.4 1594.66   656.5 1603.39     668 1608.07   691.4 1620.46
#Mann= 5 ,-1 , 0
       0      .1       0     130    .035       0   327.6      .1       0
   412.3    .045       0   480.6      .1       0
Bank Sta=412.3,480.6
XS Rating Curve= 0 ,0
Exp/Cntr=0.3,0.1

Type RM Length L Ch R = 1 ,6742    ,155.2,155.4,156.5
XS GIS Cut Line= 2
     1999079.195      173528.3631999351.82131099172978.842652269
#Sta/Elev= 30
       0 1540.09    12.7 1535.75    34.8 1530.56      53 1529.63      75 1526.13
   152.3 1518.56   210.5 1515.43     233 1512.19   291.8 1513.37     331 1511.85
   342.3 1513.62   367.1 1514.09   392.2 1511.01   399.5 1509.46   412.5 1509.21
     427  1510.1   433.9 1511.63   448.3 1512.03   459.5 1510.71   472.9 1510.49
   477.9 1511.48   485.2 1514.92   492.6 1522.23   507.1 1541.82   518.1 1554.28
   529.5 1563.65   543.9 1579.19   583.1 1613.44   603.3 1633.34   613.4 1642.26
#Mann= 5 ,-1 , 0
       0      .1       0     150    .035       0     260      .1       0
   392.2    .045       0     427      .1       0
Bank Sta=392.2,427
XS Rating Curve= 0 ,0
Exp/Cntr=0.3,0.1

Type RM Length L Ch R = 1 ,6587    ,205.3,219.4,234.8
XS GIS Cut Line= 3
 1999235.9670803173563.8742742431999304.40258523173421.186240906
1999471.94964375173086.422065337
#Sta/Elev= 30
       0 1562.47    55.7 1537.29    69.4 1528.55    84.2 1526.44    91.6  1521.9
    95.7  1520.7   128.5 1515.74   165.3 1511.57   197.1 1509.96   227.2 1511.15
   234.6 1510.04   250.9 1510.23     268 1511.68     297 1511.61   307.1 1509.79
   315.3 1511.29   327.5 1510.72   346.3 1512.46     363 1509.49     396 1508.34
   407.4 1509.49     429 1512.42   432.7 1514.07   436.4 1519.58   444.7  1535.6
   448.9 1541.66   465.7 1557.91   480.7 1570.55   498.7 1583.58   532.6 1605.85
#Mann= 5 ,-1 , 0
       0      .1       0      80    .035       0  158.25      .1       0
     363    .045       0   407.4      .1       0
Bank Sta=363,407.4
XS Rating Curve= 0 ,0
Exp/Cntr=0.3,0.1

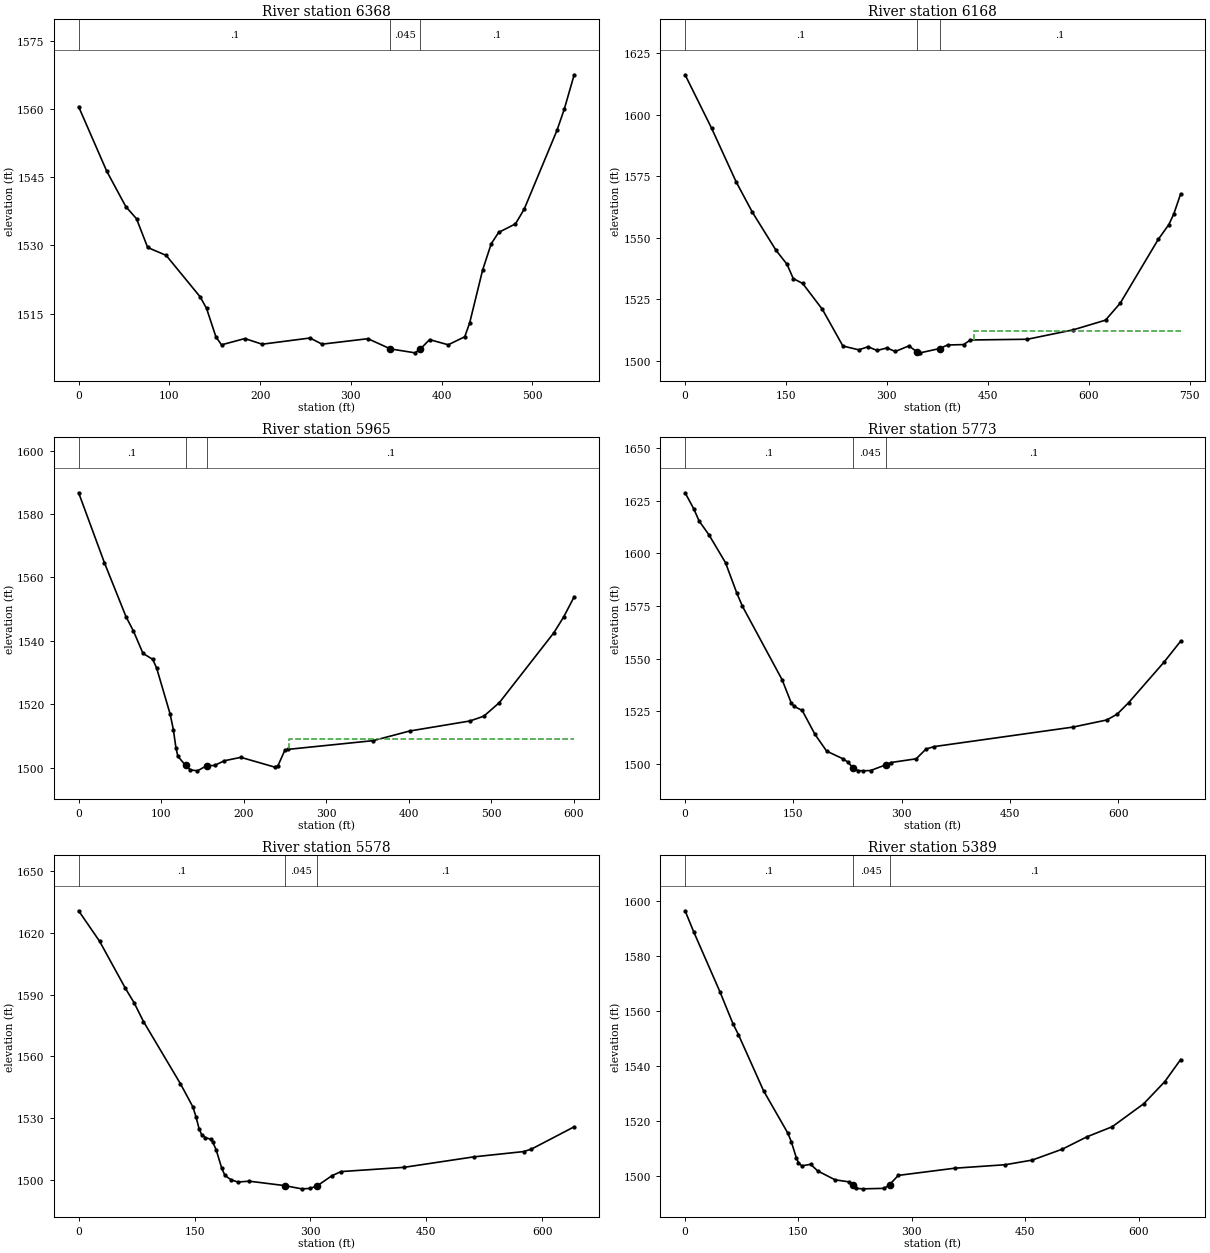
Type RM Length L Ch R = 1 ,6368    ,190.6,199.4,209.5
XS GIS Cut Line= 4
1999306.00904185173600.8770585231999396.59886891173479.673366851
1999628.87479713173318.5975975361999684.08995474173220.859551892
#Sta/Elev= 30
       0 1560.52      31 1546.33      52 1538.55    63.8 1535.88    76.1 1529.56
    96.5 1527.82     134 1518.69     141 1516.16   151.3 1509.92   157.5 1508.15
   183.2 1509.53   202.3 1508.29     255 1509.65   268.3  1508.3   318.9  1509.5
   343.7 1507.25   370.8 1506.39   376.7 1507.24   386.8  1509.3   407.4 1508.16
   425.6 1509.93     431 1512.97   445.3 1524.61   454.8 1530.39     463 1532.88
   481.5 1534.75   491.1 1537.98   527.2 1555.29   535.3 1559.98   546.2 1567.54
#Mann= 3 ,-1 , 0
       0      .1       0   343.7    .045       0   376.7      .1       0
Bank Sta=343.7,376.7
XS Rating Curve= 0 ,0
Exp/Cntr=0.3,0.1

Type RM Length L Ch R = 1 ,6168    ,219.6,202.8,188.6
XS GIS Cut Line= 4
1999360.82528939173736.8649900471999483.43715667173584.392951117
1999812.03988679173500.882369094 1999895.9789245173317.159592798
#Sta/Elev= 30
       0 1616.15    39.5 1594.38    75.9 1572.65   100.1 1560.27   135.1 1544.87
   151.5 1539.17   160.8 1533.36   174.8 1531.38   204.2 1520.81   234.6 1505.96
   258.3 1504.41   271.9 1505.66   285.4 1504.15   299.9 1505.17   312.5 1503.75
   332.8 1506.02   344.81503.541   349.5 1503.19   378.31504.933   390.3 1506.38
     414 1506.54   424.2 1508.41   508.8 1508.71     577 1512.53     625 1516.47
   646.9 1523.37   703.3 1549.24   719.1 1555.26   726.5 1559.59   736.7 1567.76
#Mann= 3 ,-1 , 0
       0      .1       0   344.8    .045       0   378.3      .1       0
#XS Ineff= 2 , 0
                             430            1512
Permanent Ineff=
       F       F
Bank Sta=344.8,378.3
XS Rating Curve= 0 ,0
Exp/Cntr=0.3,0.1

Type RM Length L Ch R = 1 ,5965    ,199.4,192.3,188.8
XS GIS Cut Line= 3
1999609.03212989173848.5135342681999878.22002519173487.239424625
1999962.78240966173363.345018372
#Sta/Elev= 30
       0 1586.71    31.2 1564.67    57.5 1547.55    66.3 1543.15      78 1536.03
    89.8 1534.14    94.5 1531.42   110.9 1516.87   114.8 1511.97   117.9 1506.25
   120.2 1503.61   129.6 1500.67   135.2 1499.28     144 1498.97     155 1500.56
   164.8 1500.68   176.5 1502.15   196.6 1503.23   237.5 1500.16   241.6 1500.62
   249.8 1505.41   253.9 1505.75     357  1508.5   401.2 1511.54   474.1  1514.7
     491 1516.21   509.9 1520.51   575.9 1542.55   587.8 1547.54   600.5 1553.89
#Mann= 3 ,-1 , 0
       0      .1       0   129.6    .045       0     155      .1       0
#XS Ineff= 2 , 0
                             255            1509
Permanent Ineff=
       F       F
Bank Sta=129.6,155
XS Rating Curve= 0 ,0
Exp/Cntr=0.3,0.1

Type RM Length L Ch R = 1 ,5773    ,172.6,195.4,211.5
XS GIS Cut Line= 4
1999745.30980436174005.4408577681999842.47527383173884.697221578
1999979.72470909173520.3430901572000038.70058693173390.986018372
#Sta/Elev= 30
       0 1628.83    12.2 1621.08    19.3 1615.49    33.2 1608.75      56 1595.57
    71.7 1581.07    79.5 1574.82   134.4 1539.93   146.9    1529   151.1 1527.24
   162.3  1525.3   179.8 1514.02   196.1 1505.97   219.1 1502.26   225.4 1500.79
   232.4 1498.12   239.4 1496.72   246.4  1496.6     257 1496.75   278.8 1499.56
     285 1500.55   320.1 1502.32   333.7 1506.93   344.6 1508.11   537.4 1517.41
   584.1 1520.78   598.5 1523.53   614.4    1529   663.4 1548.26   686.5 1558.26
#Mann= 3 ,-1 , 0
       0      .1       0   232.4    .045       0   278.8      .1       0
Bank Sta=232.4,278.8
XS Rating Curve= 0 ,0
Exp/Cntr=0.3,0.1

Type RM Length L Ch R = 1 ,5578    ,195.7,189,182.8
XS GIS Cut Line= 4
1999857.43202178174081.2679179951999962.80703674173929.505217423
2000159.95794958173799.4904740422000231.39717216173591.110586933
#Sta/Elev= 30
       0 1630.75    27.2 1615.89    60.5  1593.1    71.9 1585.99    83.9 1576.96
   131.8 1546.69   147.8 1535.51   151.8 1530.74   155.8 1524.96   159.2 1521.99
   163.8 1520.59     171 1519.78   173.3 1518.62     178 1514.58   185.1  1505.8
   189.2 1502.25   196.9 1500.17     206 1498.99   220.6 1499.42   266.7 1497.25
   288.5 1495.69   298.8 1495.86   308.2 1497.02   327.8 1502.08   339.6 1504.07
   420.9 1506.13   511.5 1511.23   575.8 1513.79   585.9 1514.99   641.2 1525.82
#Mann= 3 ,-1 , 0
       0      .1       0   266.7    .045       0   308.2      .1       0
Bank Sta=266.7,308.2
XS Rating Curve= 0 ,0
Exp/Cntr=0.3,0.1

Type RM Length L Ch R = 1 ,5389    ,135.4,154.5,188.1
XS GIS Cut Line= 3
1999970.55508201174160.0776437522000087.09182102174098.770021779
     2000458.978       173729.53
#Sta/Elev= 30
       0 1596.52    11.3 1588.92    46.3 1566.94    63.3 1555.47    70.6 1551.47
   103.9 1531.03     136 1515.64   140.6 1512.51   147.2 1506.68   149.9 1504.97
   154.5 1503.75   166.1 1504.34   175.4 1501.94   198.4 1498.69   217.2 1497.93
   221.8 1496.95   226.5 1495.56   235.7 1495.41   263.6 1495.59   270.5 1496.92
   282.1  1500.3   356.7 1502.91   423.6 1504.18   459.2 1505.86   499.3 1509.86
   531.7 1514.33   565.2    1518   606.9 1526.36   634.8 1534.42   655.7 1542.43
#Mann= 3 ,-1 , 0
       0      .1       0   221.8    .045       0   270.5      .1       0
Bank Sta=221.8,270.5
XS Rating Curve= 0 ,0
Exp/Cntr=0.3,0.1