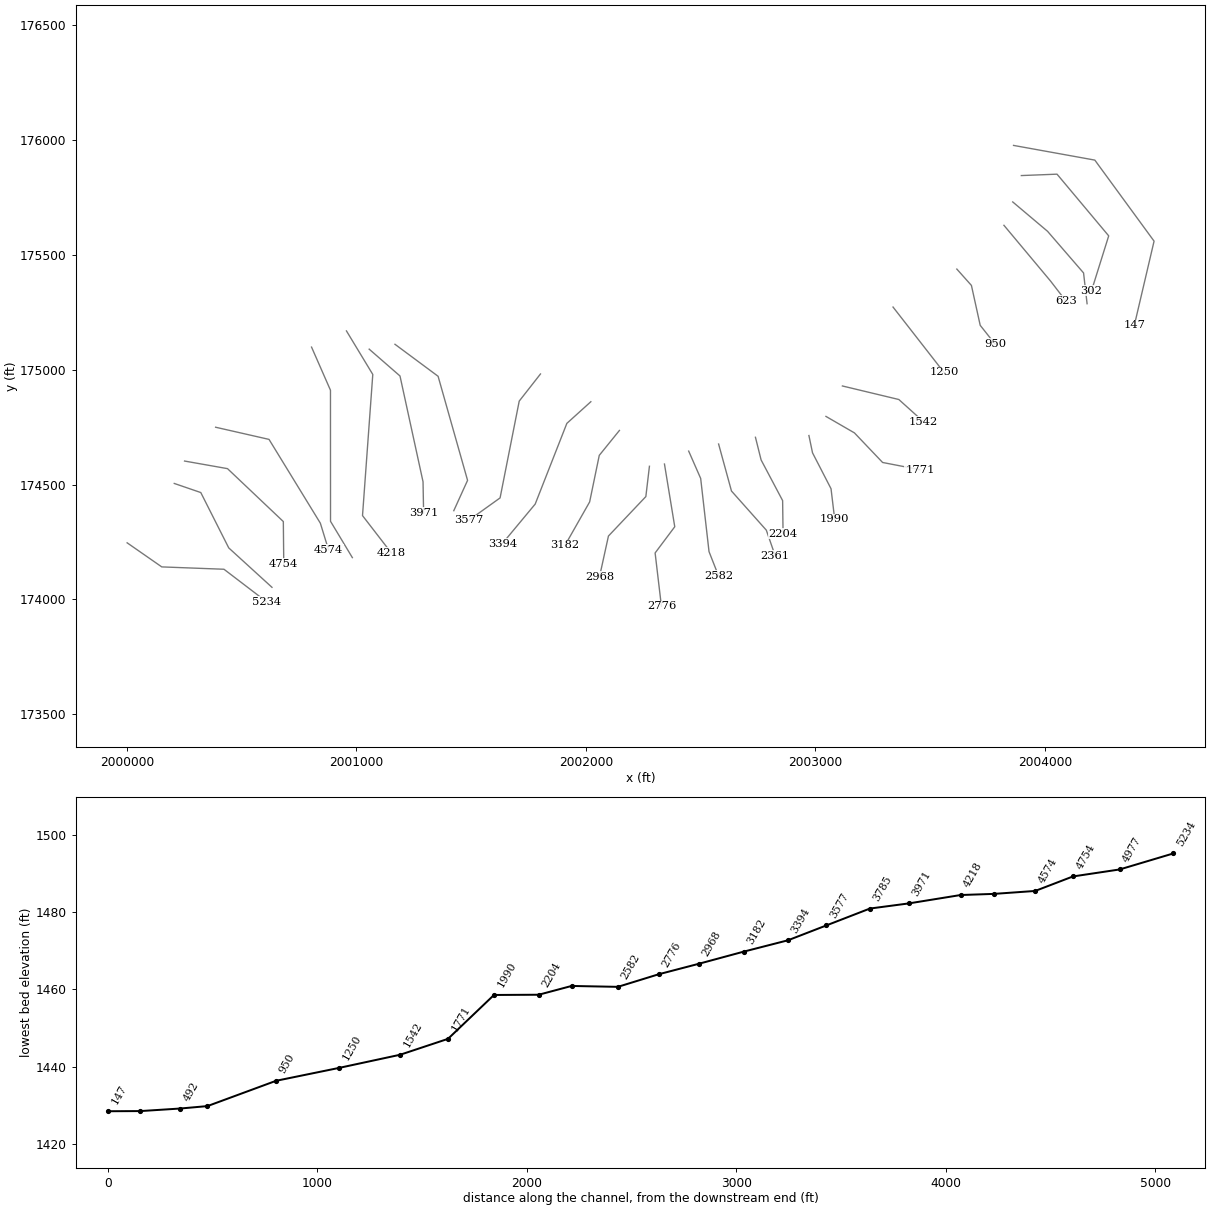
HEC-RAS study LICKCK.prj: LICKCK

--- LICKCK.g01 (geometry) --- (continued)

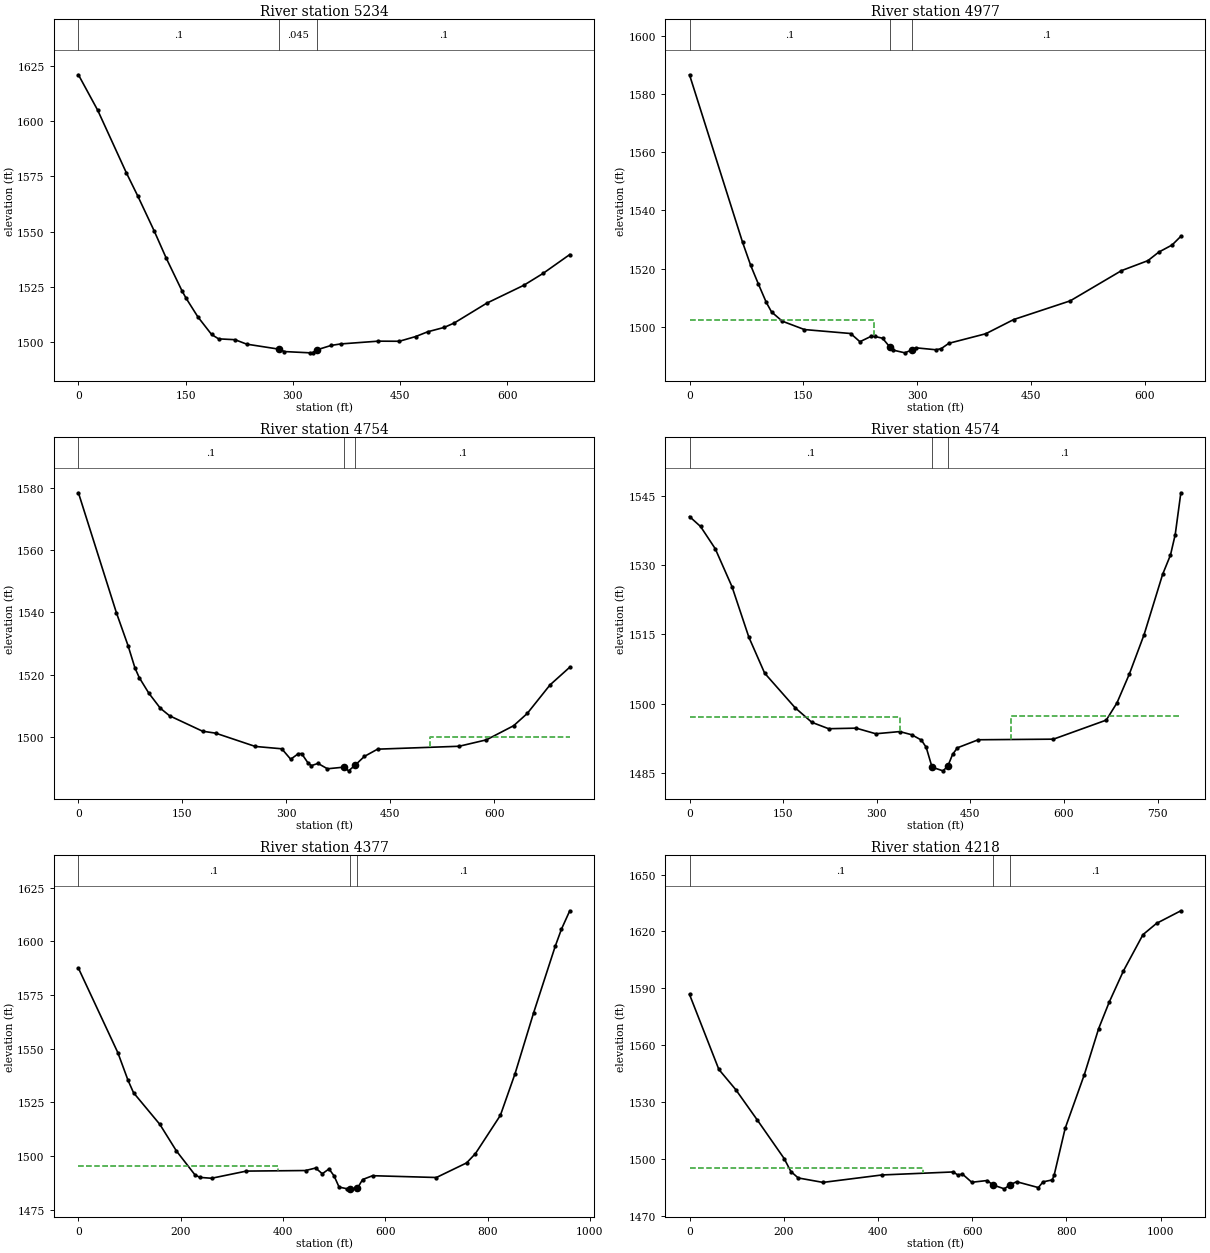
Type RM Length L Ch R = 1 ,5234    ,283.5,256.8,216.9
XS GIS Cut Line= 4
2000001.01923553174245.9734809682000151.88385156174141.057478954
2000422.86302575174130.8261962972000607.64369299173989.806460516
#Sta/Elev= 30
       0 1620.85      27 1604.81    66.9 1576.65    82.9 1566.15     106 1550.27
   122.9 1537.93   144.8 1523.26   150.7 1519.82   167.2 1511.38   186.3 1503.47
   196.1 1501.49   219.1 1501.11   235.5 1499.09   281.2  1496.8   288.1 1495.75
   324.2 1495.17   327.5 1495.28     334 1496.56   353.7 1498.53   366.9 1499.19
   419.4 1500.45   448.9  1500.4   471.7 1502.52   488.7 1504.69   511.8 1506.67
   525.8 1508.66   571.2 1517.61   623.1 1525.71   649.9 1531.04   687.4  1539.6
#Mann= 3 ,-1 , 0
       0      .1       0   281.2    .045       0     334      .1       0
Bank Sta=281.2,334
XS Rating Curve= 0 ,0
Exp/Cntr=0.3,0.1

Type RM Length L Ch R = 1 ,4977    ,216.8,223.1,229.3
XS GIS Cut Line= 4
2000206.37541579174504.6037848522000321.89372344  174464.9952078
2000443.65790612174223.8493924262000632.07172925 174052.02957776
#Sta/Elev= 30
       0 1586.57    69.9 1529.01    80.6 1521.08    90.7 1514.69   101.2 1508.33
   108.1 1505.07   122.1 1501.91   151.4 1499.02   212.3 1497.66   224.5 1494.84
   239.1 1496.68     244 1496.66   254.3 1496.04   263.6 1493.12   268.4 1491.95
   283.7 1491.02   292.9 1492.03   292.9 1492.05   298.4 1492.74   324.6 1492.08
   331.5 1492.45   341.7  1494.3   390.3 1497.58   427.1 1502.46   501.6 1508.89
   569.1 1519.27   603.9  1522.7   618.2 1525.63   635.7 1528.07   647.3 1531.06
#Mann= 3 ,-1 , 0
       0      .1       0   263.6    .045       0   292.9      .1       0
#XS Ineff= 2 , 0
          243.32 1502.46
Permanent Ineff=
       F       F
Bank Sta=263.6,292.9
XS Rating Curve= 0 ,0
Exp/Cntr=0.3,0.1

Type RM Length L Ch R = 1 ,4754    ,185.7,180.2,173.8
XS GIS Cut Line= 4
2000251.22745205174602.2376035462000438.29687896 174569.14539958
2000681.52434529174338.5910789692000683.39510677174154.494439162
#Sta/Elev= 30
       0 1578.37    54.9 1539.86    71.6 1529.38    81.6  1522.2    87.8  1519.1
   101.6 1514.12   118.2 1509.29   131.6 1506.86   179.1 1501.92   198.1 1501.29
   255.3 1497.03   293.5 1496.28   306.4 1492.93   317.3 1494.69   322.1 1494.76
   331.9 1491.57   336.4 1490.89   345.8 1491.59   359.4 1489.87     383 1490.39
     390 1489.21   399.2 1490.98   412.7 1493.83   431.8 1496.16   549.5 1497.09
   588.9 1499.15   628.2 1503.68   647.8  1507.6   680.7 1516.76   709.2 1522.44
#Mann= 3 ,-1 , 0
       0      .1       0     383    .045       0   399.2      .1       0
#XS Ineff= 2 , 0
                             508            1500
Permanent Ineff=
       F       F
Bank Sta=383,399.2
XS Rating Curve= 0 ,0
Exp/Cntr=0.3,0.1

Type RM Length L Ch R = 1 ,4574    ,207.5,197,183.1
XS GIS Cut Line= 4
2000386.52256551174749.5616002742000619.14435665174696.592104858
2000842.80656487174331.4980322332000878.20791257174216.332417808
#Sta/Elev= 30
       0 1540.45    17.7  1538.3    41.2  1533.5    68.1 1525.28    95.1 1514.36
   120.4 1506.58   169.1 1499.12     196 1495.95   222.9 1494.57     267 1494.69
   298.4 1493.48   336.9 1493.95   356.1 1493.26   371.5 1492.11   379.2 1490.55
   388.6 1486.25   406.1 1485.46   413.8 1486.46   421.5 1489.02   429.2 1490.44
   462.6 1492.18   583.1 1492.31   667.7 1496.43   684.8 1500.14   704.7  1506.4
   728.3 1514.91     758 1527.95   770.6 1532.13   778.2 1536.56   787.2 1545.59
#Mann= 3 ,-1 , 0
       0      .1       0   388.6    .045       0   413.8      .1       0
#XS Ineff= 2 , 0
          337.58 1497.06  515.15         1497.24
Permanent Ineff=
       F       F
Bank Sta=388.6,413.8
XS Rating Curve= 0 ,0
Exp/Cntr=0.3,0.1

Type RM Length L Ch R = 1 ,4377    ,156.8,158.6,158
XS GIS Cut Line= 4
2000804.45539435175098.6324091012000886.88346865 174910.86985488
2000887.10780382174339.6452083332000982.21281017174181.522778862
#Sta/Elev= 30
       0 1587.51    77.1 1548.14    97.1 1535.21   107.8 1529.47   159.3 1514.71
   191.6 1502.36   227.6  1491.3   237.4 1490.03   260.4 1489.63   328.4 1492.97
   444.1 1493.23   463.8  1494.4   476.9 1491.73     490 1493.97   499.9 1490.74
   509.7 1485.52   526.1  1484.7   530.61484.733   545.51484.964   555.7 1489.04
   575.3 1490.82     700 1489.98   759.1 1496.79   776.3 1501.11   825.1 1518.94
   853.8 1538.36   890.2 1566.78   932.3 1597.67   944.6 1605.72   960.8 1614.25
#Mann= 3 ,-1 , 0
       0      .1       0   530.6    .045       0   545.5      .1       0
#XS Ineff= 2 , 0
          391.21 1495.45
Permanent Ineff=
       F       F
Bank Sta=530.6,545.5
XS Rating Curve= 0 ,0
Exp/Cntr=0.3,0.1

Type RM Length L Ch R = 1 ,4218    ,238.5,247.6,254.9
XS GIS Cut Line= 4
2000956.54448107175169.1037162612001071.25252689174979.521914577
2001026.47455109174364.5191299962001151.69889924174202.343367271
#Sta/Elev= 30
       0 1586.83    62.3 1547.33    98.1  1536.7   144.1 1520.61   200.9 1500.38
   215.2 1493.53   230.8 1490.15   283.4  1487.8   408.4 1491.72   559.8 1493.31
   569.6 1491.72   579.4 1492.19   599.2 1487.87   632.1  1488.8   643.61486.523
   668.3 1484.41   680.31486.535   694.5 1488.16   740.6 1485.07   750.5 1488.08
   770.2 1489.12   774.3 1491.81   797.5 1516.28   838.2 1544.58   868.6 1568.83
   890.9 1582.71   921.3 1599.27   962.7 1618.33   991.5 1624.27  1043.1  1630.9
#Mann= 3 ,-1 , 0
       0      .1       0   643.6    .045       0   680.3      .1       0
#XS Ineff= 2 , 0
             495 1495.28
Permanent Ineff=
       F       F
Bank Sta=643.6,680.3
XS Rating Curve= 0 ,0
Exp/Cntr=0.3,0.1

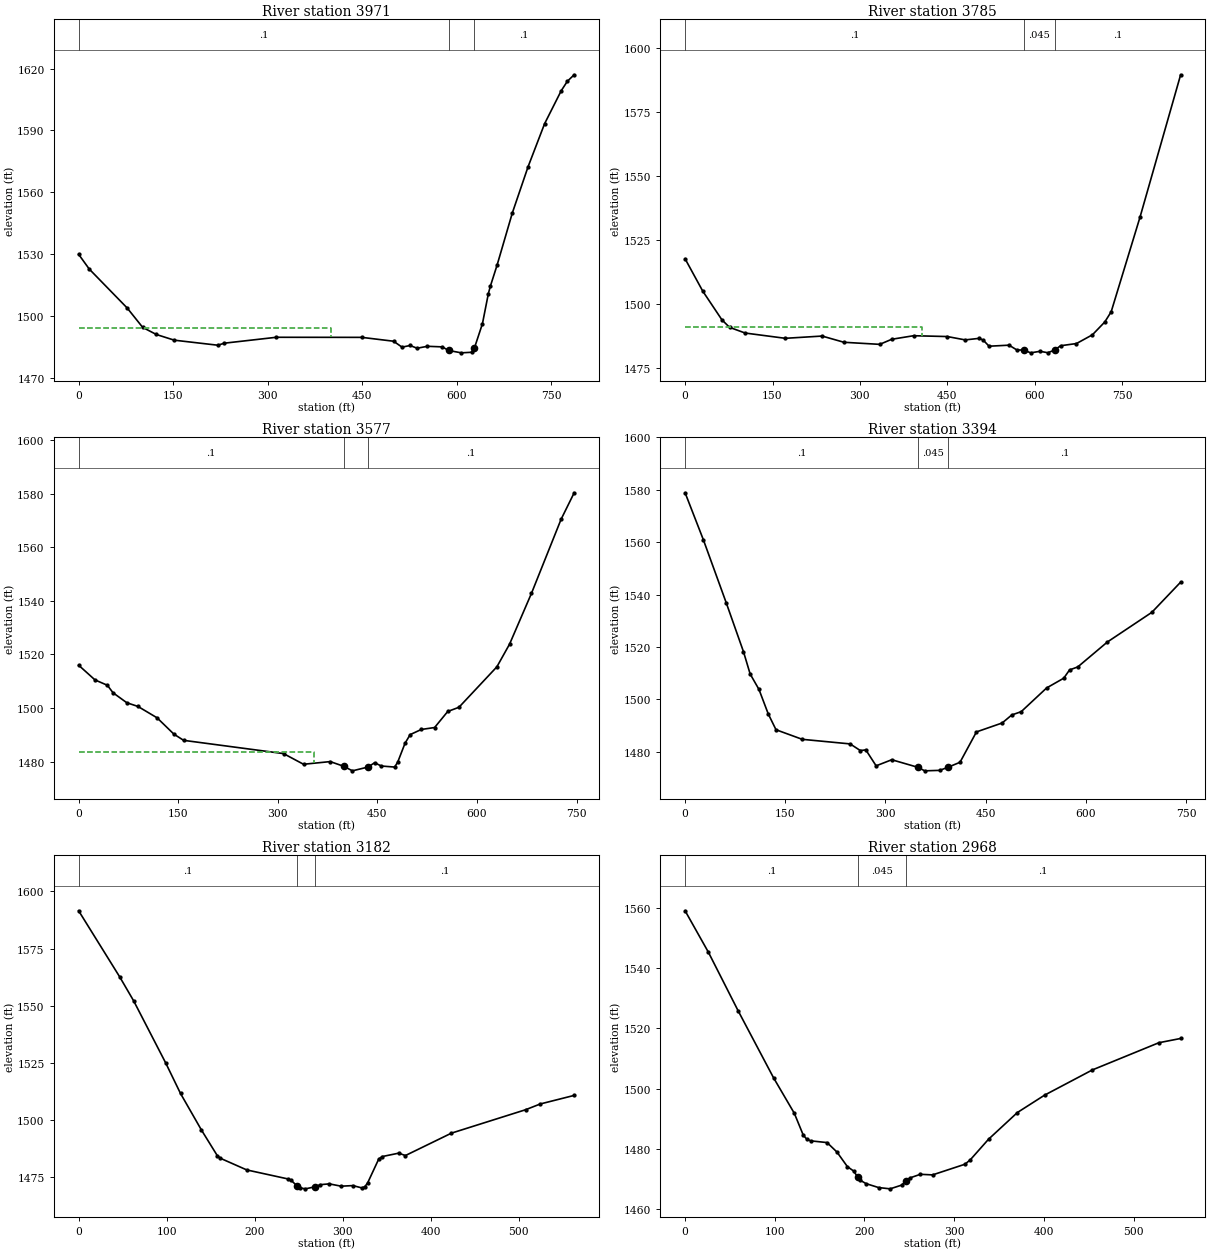
Type RM Length L Ch R = 1 ,3971    ,184.5,185.8,187.7
XS GIS Cut Line= 4
2001055.50105345175089.7530736512001189.78315294174972.833158516
 2001290.1841829174511.9393751252001292.67759819174375.644055197
#Sta/Elev= 30
       0 1529.98    16.9 1522.82    76.9 1504.01   101.6 1494.58   123.3 1491.13
   151.8 1488.37   220.9 1485.93   230.9 1486.91   313.6 1489.78   449.2 1489.74
   499.6 1487.87     513    1485   525.9  1485.8   536.9 1484.47   553.3 1485.41
   576.8 1485.13   586.9 1483.39     607 1482.24   623.8 1482.52   627.9 1484.62
   640.6 1496.38     650 1510.97   653.2 1514.59   663.8 1524.73     688 1550.03
     713 1572.45   739.2 1593.29   765.5 1609.23   775.3 1613.85   786.1 1616.99
#Mann= 3 ,-1 , 0
       0      .1       0   586.9    .045       0   627.9      .1       0
#XS Ineff= 2 , 0
          401.13 1494.07
Permanent Ineff=
       F       F
Bank Sta=586.9,627.9
XS Rating Curve= 0 ,0
Exp/Cntr=0.3,0.1

Type RM Length L Ch R = 1 ,3785    ,221.3,207.7,187.9
XS GIS Cut Line= 4
2001167.93092298175110.9196957062001355.78716641174971.536252161
2001484.17970999174518.1332229252001424.17791056174385.964823891
#Sta/Elev= 30
       0 1517.61    30.3 1504.99    63.1 1493.82    76.2 1490.87     103 1488.64
   171.9 1486.58   235.1 1487.46   272.6 1485.03     334 1484.22   354.5  1486.2
     392 1487.59   449.9 1487.27   480.6 1485.96   504.5 1486.56   511.3 1485.93
   521.6  1483.5   555.9  1483.9   569.3 1482.03   580.9    1482     593 1480.91
   609.1 1481.51   622.4 1480.95   634.1    1482   644.3 1483.68   671.6 1484.54
   698.9 1487.95   720.1 1492.94   731.1 1496.93   780.7 1533.95   850.3 1589.43
#Mann= 3 ,-1 , 0
       0      .1       0   580.9    .045       0   634.1      .1       0
#XS Ineff= 2 , 0
          407.32 1491.01
Permanent Ineff=
       F       F
Bank Sta=580.9,634.1
XS Rating Curve= 0 ,0
Exp/Cntr=0.3,0.1

Type RM Length L Ch R = 1 ,3577    ,188.2,183.6,177.3
XS GIS Cut Line= 4
2001801.80831656174981.5832900082001709.23554277174863.446272384
2001625.83880832174441.6379956732001490.63766108174344.842758904
#Sta/Elev= 30
       0 1515.96    24.6 1510.48    43.3 1508.47    51.8 1505.68    72.6 1501.95
    89.3 1500.58   118.1 1496.34   143.5 1490.24   158.1 1487.93   308.6 1482.98
   338.7    1479   378.9    1480   399.5 1478.23   412.3 1476.55   435.7 1477.96
   445.8 1479.57   455.8 1478.35   475.9 1477.96   480.5 1479.77   491.6 1486.86
   499.3 1490.06     516 1491.98   536.1 1492.71   555.9  1498.7   572.8 1500.27
   629.9 1515.36     649 1523.82     682 1542.78   726.6  1570.4   746.3 1580.29
#Mann= 3 ,-1 , 0
       0      .1       0   399.5    .045       0   435.7      .1       0
#XS Ineff= 2 , 0
             355  1483.5
Permanent Ineff=
       F       F
Bank Sta=399.5,435.7
XS Rating Curve= 0 ,0
Exp/Cntr=0.3,0.1

Type RM Length L Ch R = 1 ,3394    ,203.7,211.7,216.5
XS GIS Cut Line= 4
2002021.28921104174860.7326205482001916.69353508 174766.26495373
2001778.84837107174414.8223668822001636.02868554174242.980379452
#Sta/Elev= 30
       0 1578.85    27.3 1560.94    61.6 1536.84    87.4 1518.19    97.4 1509.67
   110.6 1503.78   124.5 1494.42   136.1 1488.39   175.4 1484.73   247.1 1482.98
   262.3 1480.45   270.6 1480.69     286 1474.61   309.4 1476.94   348.9 1474.02
   358.7  1472.7   381.2 1472.88   393.9  1474.1   411.6 1475.97   436.2 1487.56
   474.7 1490.97   489.1 1494.03   503.2 1495.29   541.3 1504.35   566.9 1508.07
   575.6 1511.23   587.9 1512.37   632.2 1521.88   698.8 1533.21   741.9 1544.73
#Mann= 3 ,-1 , 0
       0      .1       0   348.9    .045       0   393.9      .1       0
Bank Sta=348.9,393.9
XS Rating Curve= 0 ,0
Exp/Cntr=0.3,0.1

Type RM Length L Ch R = 1 ,3182    ,227.5,214.2,202.2
XS GIS Cut Line= 4
2002145.79148078174735.6065311052002057.98552319174627.040653247
 2002016.0393529174424.1134116042001909.21500209174236.023028646
#Sta/Elev= 30
       0 1591.53    46.8  1562.5    62.5 1552.11    98.9 1524.93   115.8 1511.52
   139.6  1495.5   157.6 1484.29   160.9 1483.18   191.1 1478.04     238 1474.09
   241.3 1473.58     248 1471.11   251.4 1470.17   257.8 1469.76   268.1 1470.61
   274.8 1471.59   284.9 1471.94   298.3 1470.92   311.7 1471.18   321.7 1470.19
   325.1 1470.62   328.4 1472.31   341.1 1482.83   345.2 1483.91   363.8 1485.39
   371.4 1484.34   423.7 1494.15   507.9 1504.39   524.7 1506.93   563.2 1510.68
#Mann= 3 ,-1 , 0
       0      .1       0     248    .045       0   268.1      .1       0
Bank Sta=248,268.1
XS Rating Curve= 0 ,0
Exp/Cntr=0.3,0.1

Type RM Length L Ch R = 1 ,2968    ,187,191.5,195.1
XS GIS Cut Line= 4
2002276.54968135174579.4812369072002260.89077498174447.423336825
2002097.96081739174275.5337559882002058.82077917174097.079354996
#Sta/Elev= 30
       0 1559.19      26 1545.38      59 1525.97    98.6  1503.6   121.8 1491.76
   131.7 1484.54   135.7 1483.12   140.2 1482.59   158.3 1482.02   169.3 1478.88
   180.9 1474.03   187.9 1472.55   192.5 1470.52   195.3 1469.48   201.8 1468.35
   215.7 1467.05   228.6 1466.62   241.3 1467.85   245.9  1469.1   250.6 1470.25
   262.3 1471.46   275.9 1471.26     312 1474.81   317.9 1476.26   338.3 1483.13
   370.5 1492.03   400.8 1497.81   454.1 1506.21   528.2 1515.26   552.5 1516.68
#Mann= 3 ,-1 , 0
       0      .1       0   192.5    .045       0   245.9      .1       0
Bank Sta=192.5,245.9
XS Rating Curve= 0 ,0
Exp/Cntr=0.3,0.1

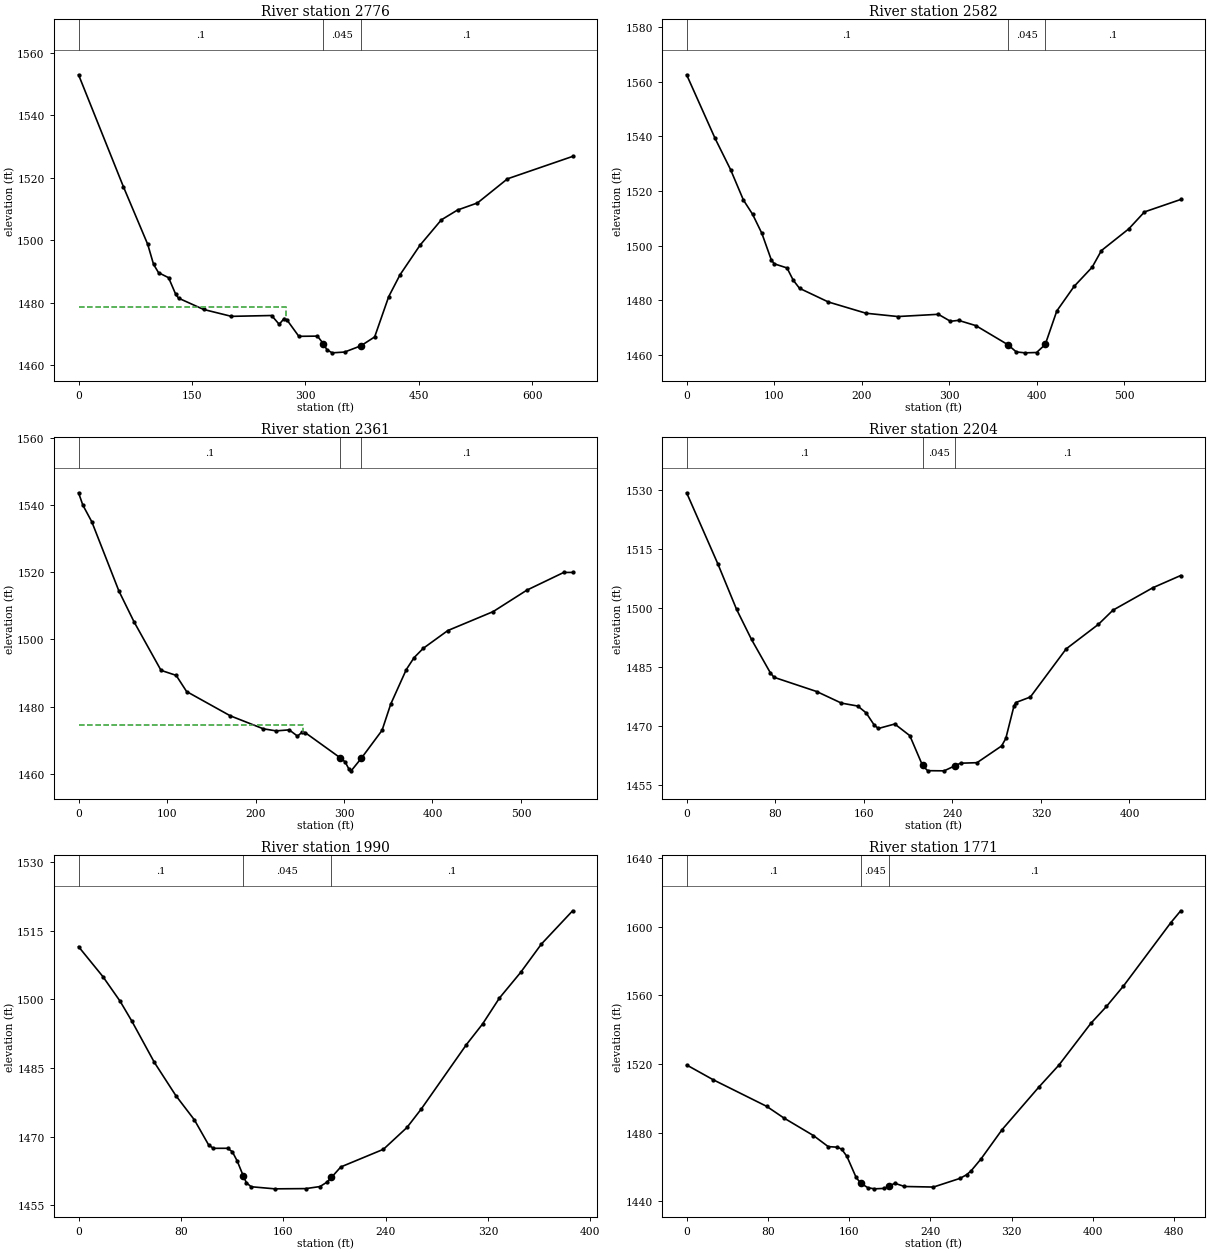
Type RM Length L Ch R = 1 ,2776    ,166.5,194.5,219.4
XS GIS Cut Line= 4
2002342.01432845174589.2201558432002386.85044025174316.002566035
2002301.28343443174201.7862304852002328.74778336173969.423064988
#Sta/Elev= 30
       0 1552.99    59.3 1517.14    91.5 1498.66    99.2 1492.27   105.8 1489.59
   119.1 1487.98   128.6 1482.62   132.4 1481.41   165.5  1477.8   202.2  1475.6
   255.4 1475.87   265.4 1473.05     272 1474.91   275.4 1474.55   291.4  1469.2
     316 1469.27   323.7 1466.88   328.6 1464.89   335.5 1463.91   351.9 1464.16
   373.4 1466.15   391.7 1469.01   410.3 1481.93   425.3 1488.93   451.7 1498.39
   479.9 1506.51   501.3 1509.66   527.7 1511.93   567.4 1519.66   653.6 1526.84
#Mann= 3 ,-1 , 0
       0      .1       0   323.7    .045       0   373.4      .1       0
#XS Ineff= 2 , 0
          274.48 1478.47
Permanent Ineff=
       F       F
Bank Sta=323.7,373.4
XS Rating Curve= 0 ,0
Exp/Cntr=0.3,0.1

Type RM Length L Ch R = 1 ,2582    ,200.6,221,238.7
XS GIS Cut Line= 4
2002447.53774843174645.604492668  2002499.781447174526.413188541
2002536.15622921174207.5951418622002577.66434776174101.847994989
#Sta/Elev= 30
       0 1562.61    32.5 1539.29    50.2 1527.85    64.9 1516.68    75.3  1511.5
      86 1504.45    96.8  1494.7   100.3 1493.28   114.7 1491.79   121.8 1487.31
     129 1484.32     162  1479.3     205 1475.18   241.4 1473.97   287.6 1474.79
   301.5 1472.23   310.7 1472.57   330.5 1470.64     367 1463.67   376.7    1461
   386.6 1460.66   399.9 1460.78   409.8 1463.72     423 1476.01   442.8 1485.03
   463.4 1492.06     474 1498.16   505.3 1506.13   523.2 1512.33   564.6 1516.89
#Mann= 3 ,-1 , 0
       0      .1       0     367    .045       0   409.8      .1       0
Bank Sta=367,409.8
XS Rating Curve= 0 ,0
Exp/Cntr=0.3,0.1

Type RM Length L Ch R = 1 ,2361    ,163.8,157,152.3
XS GIS Cut Line= 4
2002577.88171209174676.449784771 2002633.9361216174471.709276027
2002785.81156928174301.0352367692002824.29109505174189.888860233
#Sta/Elev= 30
       0 1543.63     4.8 1539.98      15 1534.98    45.6  1514.4    62.6 1505.28
    93.2 1490.79   110.3  1489.3   122.1 1484.49   171.5 1477.26   208.9 1473.39
   223.3 1472.78   238.1 1473.08   247.4 1471.22   252.4 1472.32   256.2 1472.25
   295.7 1464.77   301.2 1463.56   305.8 1461.31   308.1 1460.89   319.7 1464.68
     343 1472.94   352.8 1480.74   370.4 1491.03   379.2 1494.57   389.5 1497.33
   417.3 1502.63   468.5 1508.26   506.7 1514.66   548.3 1519.92   558.4 1519.93
#Mann= 3 ,-1 , 0
       0      .1       0   295.7    .045       0   319.7      .1       0
#XS Ineff= 2 , 0
           254.2 1474.45
Permanent Ineff=
       F       F
Bank Sta=295.7,319.7
XS Rating Curve= 0 ,0
Exp/Cntr=0.3,0.1

Type RM Length L Ch R = 1 ,2204    ,213,213.5,219.8
XS GIS Cut Line= 4
2002738.40331446 174705.718863742002763.06700534174607.053006148
2002856.80217794174429.9210990982002858.73636479174285.770635213
#Sta/Elev= 30
       0 1529.27    28.2 1511.21    45.1 1499.66    58.6    1492    75.5 1483.59
    78.9 1482.39   117.5 1478.77   139.8 1475.83   154.6 1475.08   162.1 1473.36
   169.5 1470.23   173.2 1469.38     188 1470.52   201.6 1467.56   213.1 1459.98
   217.7 1458.66   232.6 1458.62   242.8 1459.96   247.4 1460.56   262.3 1460.69
   284.5 1464.94   288.3 1466.84   295.7 1475.11   297.3 1475.97   310.5 1477.38
   342.8  1489.6   371.9 1495.83   385.1 1499.44   421.1 1505.14   446.3 1508.25
#Mann= 3 ,-1 , 0
       0      .1       0   213.1    .045       0   242.8      .1       0
Bank Sta=213.1,242.8
XS Rating Curve= 0 ,0
Exp/Cntr=0.3,0.1

Type RM Length L Ch R = 1 ,1990    ,209.5,219.6,231.1
XS GIS Cut Line= 4
2002971.38392522174713.3745695422002987.06649869174638.068320612
 2003067.7063163174481.6132898712003083.58267925174349.307363376
#Sta/Elev= 30
       0 1511.53      19 1504.99    32.4 1499.63    41.7 1495.22    59.2 1486.24
      76 1478.97    90.6 1473.62   101.7 1468.15   105.4 1467.42   116.5 1467.43
   120.2 1466.67     124 1464.66   128.8 1461.36   131.2 1459.88   134.9 1459.02
   153.4 1458.56   177.6 1458.61   188.7 1459.06     194 1459.99   197.7 1461.07
     205 1463.35   238.3 1467.21   256.7 1471.98     268 1476.07   303.2 1490.12
   315.8 1494.62     329  1500.3   345.5 1505.88   361.8 1512.11   386.2 1519.38
#Mann= 3 ,-1 , 0
       0      .1       0   128.8    .045       0   197.7      .1       0
Bank Sta=128.8,197.7
XS Rating Curve= 0 ,0
Exp/Cntr=0.3,0.1

Type RM Length L Ch R = 1 ,1771    ,212.7,228.4,241.2
XS GIS Cut Line= 4
2003045.58186442174796.7096142632003169.68445633174724.875294198
2003292.39503886174596.0253387832003454.54068554174564.645844157
#Sta/Elev= 30
       0 1519.43      26 1510.85    78.8  1495.3    95.6 1488.57   124.9 1478.25
   139.4 1471.83   148.3 1471.49   152.6 1470.37   157.8 1466.16   166.9 1453.85
   171.4 1450.51   178.5 1447.85   184.9 1447.21   194.7 1447.47   199.4 1448.82
     205 1450.45   214.5 1448.58     243 1448.25     269 1453.27   275.6  1455.4
   280.1 1457.69   289.9 1464.67   310.7 1481.78   346.5 1506.31   366.6 1519.37
   398.1 1543.74   413.4 1553.53   430.1 1565.42   476.8 1602.41   486.5  1609.3
#Mann= 3 ,-1 , 0
       0      .1       0   171.4    .045       0   199.4      .1       0
Bank Sta=171.4,199.4
XS Rating Curve= 0 ,0
Exp/Cntr=0.3,0.1

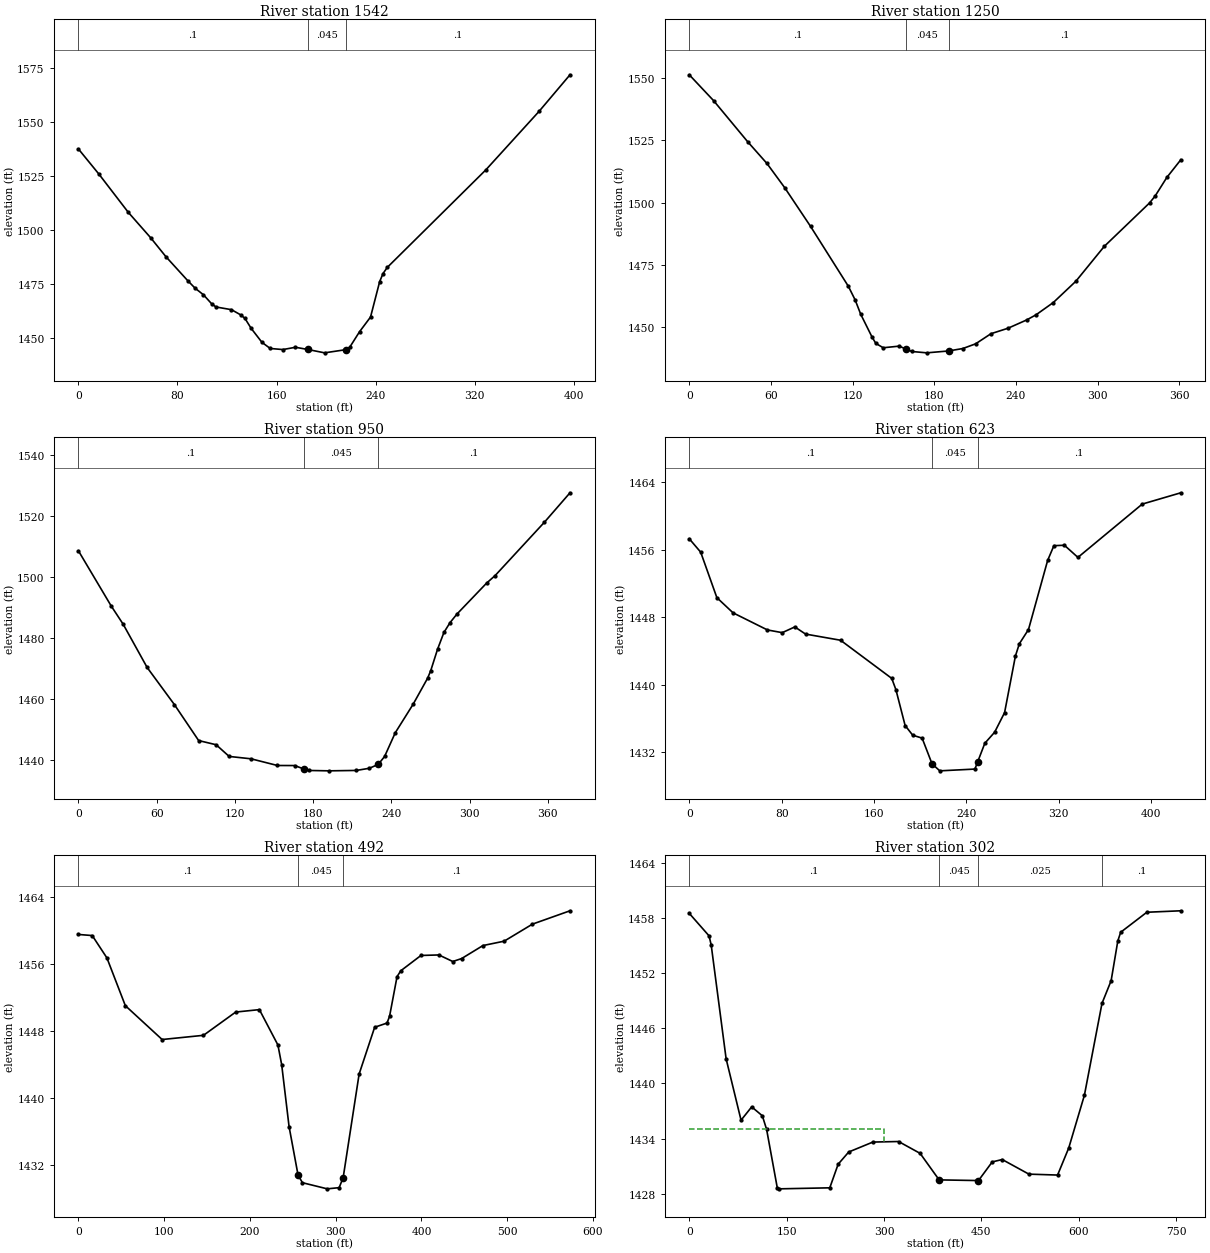
Type RM Length L Ch R = 1 ,1542    ,307.3,292.2,272.6
XS GIS Cut Line= 3
2003117.25347411174929.3229545272003363.07855912174870.355566534
2003470.29199184 174773.86347709
#Sta/Elev= 30
       0 1537.56    16.6 1525.88    40.2 1508.25    58.3 1496.45    70.6 1487.69
    88.2 1476.59    94.2 1473.07     101 1469.98   107.7 1465.76   111.1 1464.35
   123.6  1463.1   131.3 1460.61   134.5 1459.03   139.5 1454.44   148.2 1447.97
   154.9 1445.12   165.1 1444.62   175.3 1445.68   185.3 1444.65   198.8  1443.1
   216.1 1444.58     219 1445.61     227 1452.86   235.9 1459.69   243.3 1476.15
     246 1479.85   249.4 1482.67   328.9 1527.81     372 1554.99     397 1571.95
#Mann= 3 ,-1 , 0
       0      .1       0   185.3    .045       0   216.1      .1       0
Bank Sta=185.3,216.1
XS Rating Curve= 0 ,0
Exp/Cntr(USF)=0,0
Exp/Cntr=0.3,0.1

Type RM Length L Ch R = 1 ,1250    ,312.1,300.3,282.8
XS GIS Cut Line= 2
2003337.80682141175273.1717494492003559.89178918 174988.29034252
#Sta/Elev= 30
       0 1551.28    17.9 1540.89    42.8 1524.49    57.1 1515.68    70.1 1505.99
    89.1 1490.46   116.9  1466.4   121.9 1460.91     126 1455.16   134.3 1446.03
   137.1 1443.48   142.5 1441.73   154.3 1442.38   158.9 1441.27   163.6 1440.23
   174.5 1439.69   190.5 1440.44     201 1441.42   210.4  1443.3   221.7 1447.37
   234.2 1449.56   247.8 1452.86   254.8 1454.95   267.5 1459.88   284.1 1468.44
   304.9 1482.39   338.2 1499.84   342.3 1502.61   350.9 1510.07   361.2 1517.19
#Mann= 3 ,-1 , 0
       0      .1       0   158.9    .045       0   190.5      .1       0
Bank Sta=158.9,190.5
XS Rating Curve= 0 ,0
Exp/Cntr(USF)=0,0
Exp/Cntr=0.3,0.1

Type RM Length L Ch R = 1 ,950     ,312.6,327.4,348.5
XS GIS Cut Line= 4
2003615.79593623175438.5867599242003679.35818563175367.366408192
2003717.64869731175193.5274851472003781.97675694175112.351600377
#Sta/Elev= 30
       0 1508.44    25.1 1490.39    34.3  1484.4    52.7 1470.22    73.6 1458.06
    92.2 1446.28   105.6 1444.91   115.6 1441.08   132.4  1440.3   152.6 1438.11
   165.9 1438.09   172.7 1436.99   176.9 1436.48     192 1436.36   213.1 1436.49
   223.1  1437.2   229.9 1438.47   234.8 1441.06     243 1448.85   256.7 1458.19
   267.8 1466.72   270.2  1469.2   275.4 1476.18   280.3  1481.7     285 1484.92
   290.3 1487.73     313 1497.85   319.6 1500.35   357.3 1517.78     377 1527.46
#Mann= 3 ,-1 , 0
       0      .1       0   172.7    .045       0   229.9      .1       0
Bank Sta=172.7,229.9
XS Rating Curve= 0 ,0
Exp/Cntr(USF)=0,0
Exp/Cntr=0.3,0.1

Type RM Length L Ch R = 1 ,623     ,130.4,130.5,131.1
XS GIS Cut Line= 3
2003821.03307886 175629.273508112004023.97279079175386.511664034
2004090.59828112175299.975107628
#Sta/Elev= 30
       0 1457.33     9.9 1455.74    23.9 1450.35    37.9 1448.55    67.7 1446.52
    80.5  1446.2    91.4 1446.88   100.7 1446.03     131  1445.3   175.3 1440.78
   178.9 1439.45   186.9 1435.19   193.5 1434.04   201.6  1433.7   210.2 1430.65
   216.9 1429.82   247.3 1430.03   249.8 1430.92   255.9 1433.09   264.4  1434.4
     273 1436.72   282.4 1443.44   285.8 1444.89   293.7 1446.57   310.3 1454.77
   315.7 1456.51   324.8 1456.56   336.5 1455.12   392.2 1461.44   425.6 1462.78
#Mann= 3 ,-1 , 0
       0      .1       0   210.2    .045       0   249.8      .1       0
Bank Sta=210.2,249.8
XS Rating Curve= 0 ,0
Exp/Cntr(USF)=0,0
Exp/Cntr=0.3,0.1

Type RM Length L Ch R = 1 ,492     ,192.5,190.3,200.4
XS GIS Cut Line= 4
2003859.32359054 175731.126269192004010.95401681175603.235960165
2004167.94511472175421.7389347832004183.26131939175287.722143889
#Sta/Elev= 30
       0 1459.48    16.1 1459.35    33.2 1456.69    54.7    1451    97.6 1446.97
   145.8 1447.47   183.4 1450.24     211 1450.53   232.6 1446.32     237 1443.97
   245.6 1436.61   256.1 1430.82   261.2 1429.92   290.1 1429.19     304 1429.33
   308.7 1430.53   327.3 1442.86   345.4 1448.43   359.8 1448.93   362.8 1449.74
   371.5 1454.45   375.8 1455.15   399.4 1456.98   420.3 1457.04   436.5 1456.26
   446.8 1456.61   471.7 1458.16   496.4 1458.68   529.4 1460.71   573.2  1462.3
#Mann= 3 ,-1 , 0
       0      .1       0   256.1    .045       0   308.7      .1       0
Bank Sta=256.1,308.7
XS Rating Curve= 0 ,0
Exp/Cntr(USF)=0,0
Exp/Cntr=0.3,0.1

Type RM Length L Ch R = 1 ,302     ,155.2,155.2,155.2
XS GIS Cut Line= 4
2003896.84829199175845.9978042422004052.30776943175852.124286111
2004277.45597813175583.3248940892004202.40657523175343.626290948
#Sta/Elev= 30
       0 1458.51    30.5 1456.06    33.8 1455.07    56.8 1442.68    79.8    1436
    96.2 1437.45   112.6 1436.48   119.2 1434.99   135.6 1428.65   138.9 1428.53
   216.5 1428.64   229.4 1431.21   245.7 1432.54   282.9 1433.62   322.5 1433.68
   355.7 1432.39     3851429.505   445.6 1429.43   466.8 1431.46   482.2 1431.72
   523.3 1430.13   567.5 1430.03   584.7 1432.98   608.8 1438.71   635.9 1448.71
     650 1451.18   660.3 1455.51   664.7 1456.45     705 1458.63   757.4 1458.79
#Mann= 4 ,-1 , 0
       0      .1       0     385    .045       0   445.6    .025       0
  636.22      .1       0
#XS Ineff= 2 , 0
             300    1435
Permanent Ineff=
       F       F
Bank Sta=385,445.6
XS Rating Curve= 0 ,0
Exp/Cntr(USF)=0,0
Exp/Cntr=0.3,0.1

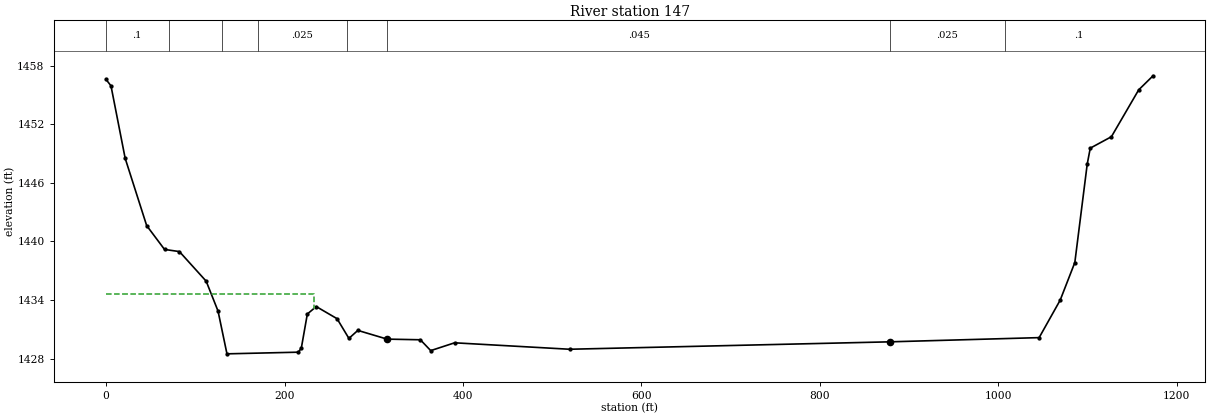
Type RM Length L Ch R = 1 ,147     ,,,
XS GIS Cut Line= 4
2003862.87730145175977.3617109032004216.95696967175913.389104805
2004475.10186322175560.2890496722004389.18415898175193.821401271
#Sta/Elev= 30
       0 1456.58     5.5 1455.93    21.4 1448.51    45.5 1441.62    65.5 1439.18
    82.2 1438.96   112.2 1435.93   125.5 1432.87   135.5 1428.49   215.6 1428.66
   218.9  1429.1   225.6 1432.57   235.6 1433.33   258.9 1432.09   272.2 1430.07
   282.2 1430.89     3151429.997   352.3 1429.93   363.9 1428.82   390.7 1429.62
   519.5 1428.96   878.8 1429.72  1045.9 1430.15  1069.5 1433.99  1085.9 1437.84
  1099.8 1447.92  1103.2 1449.55  1126.9 1450.72  1157.5 1455.52  1173.6 1456.96
#Mann= 8 ,-1 , 0
       0      .1       0      70    .025       0     130      .1       0
     170    .025       0     270      .1       0     315    .045       0
   878.8    .025       0 1007.21      .1       0
#XS Ineff= 2 , 0
          232.91 1434.64
Permanent Ineff=
       F       F
Bank Sta=315,878.8
XS Rating Curve= 0 ,0
Exp/Cntr(USF)=0,0
Exp/Cntr=0.3,0.1
LCMann Table=0

Chan Stop Cuts=-1
Use User Specified Reach Order=0
Composite Channel Slope=5